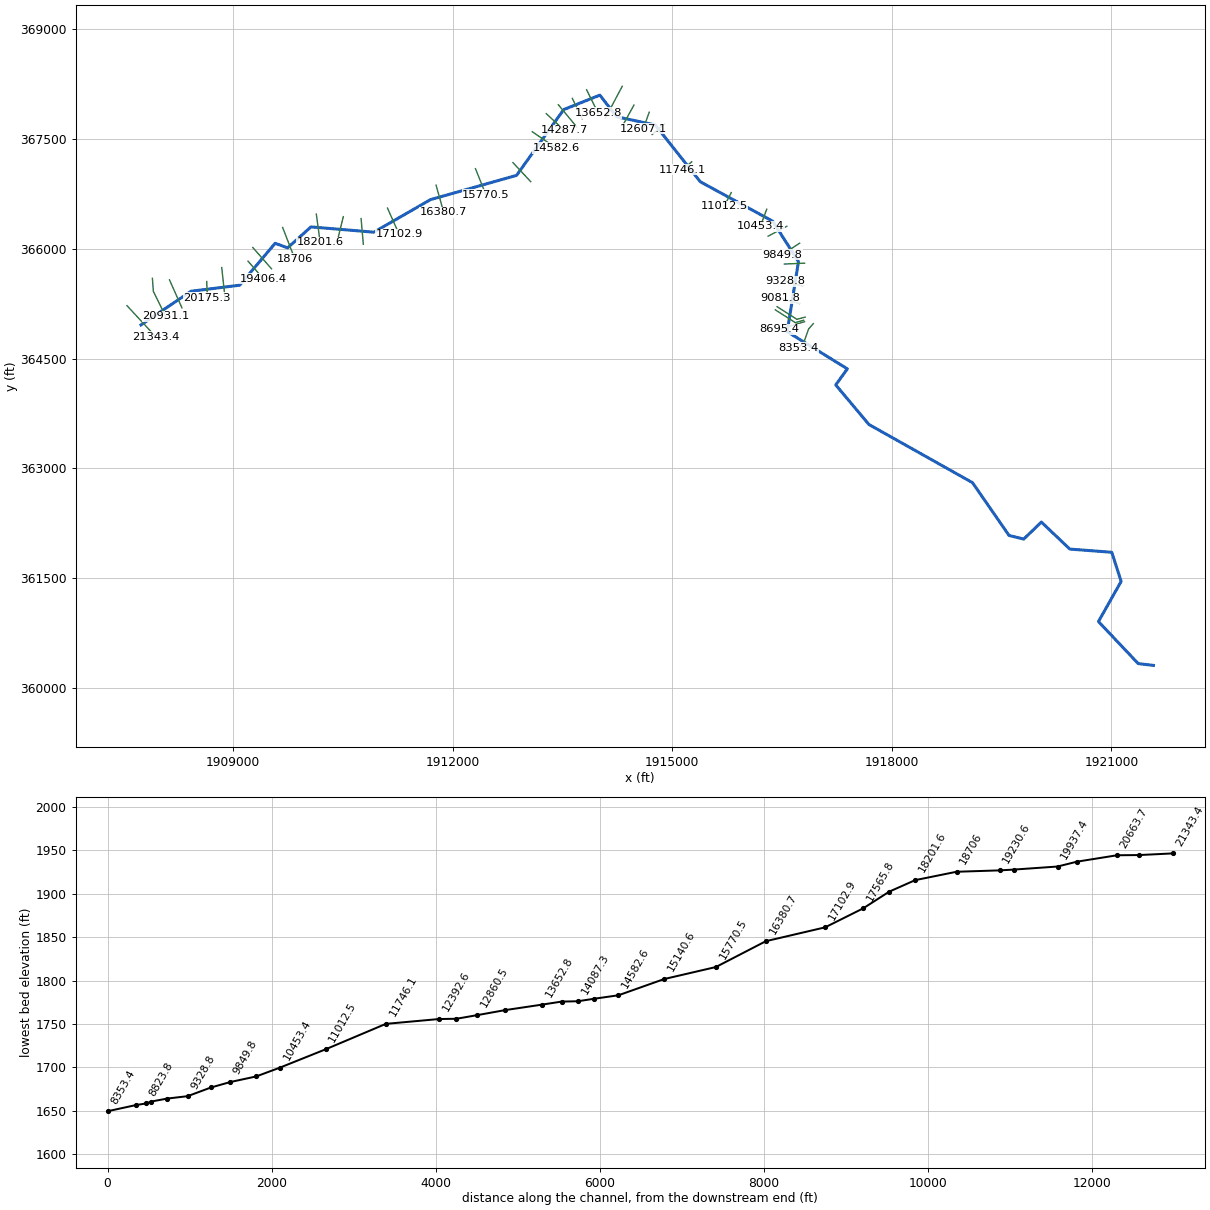
--- NP2.prj (project) ---

Proj Title=NP2
Current Plan=p01
Default Exp/Contr=0,0
English Units
Geom File=g01
Flow File=f01
Plan File=p01
BEGIN DESCRIPTION:
END DESCRIPTION:
DSS Export Rating Curves= 0
DSS Export Rating Curve Sorted= 0
DSS Export Volume Flow Curves= 0
DXF OffsetX= 0
DXF OffsetY= 0
DXF ScaleX= 0
DXF ScaleY= 0

--- NP2.p01 (plan) ---

Plan Title=Floodplain
Program Version=4.00
Geom File=g01
Flow File=f01
K Sum by GR=0
Std Step Tol=0.01
Critical Tol=0.01
Num of Std Step Trials=20
Max Error Tol=0.3
Flow Tol Ratio=0.001
Split Flow NTrial=30
Split Flow Tol=0.02
Split Flow Ratio=0.02
Log Output Level=0
Friction Slope Method=1
Unsteady Friction Slope Method=2
Unsteady Bridges Friction Slope Method=1
Global Log Level=0
CheckData=False
Run HTab=0
Run UNet=0
Run PostProcess=0
UNET Theta=0
UNET Theta Warmup=0
UNET ZTol=0
UNET ZSATol=0
UNET MxIter=0
UNET MaxInSteps=0
UNET DtIC=0
UNET DtMin=0
UNET MaxCRTS=0
UNET WFStab=0
UNET SFStab=0
UNET WFX=0
UNET SFX=0
UNET DSS MLevel=0
UNET DZMax Abort=0
UNET Convert EG Bridges=0
UNET Use Existing IB Tables=0
UNET Froude Limit=0
UNET Froude Power=0
Write IC File=0
Echo Input=False
Echo Output=False
Write Detailed=0

--- NP2.f01 (steady flow) ---

Flow Title=NFF Regression Equation
Program Version=4.10
Number of Profiles= 1
Profile Names=P100yr
River Rch & RM=NP2,Main            ,21343.4
  610.34
River Rch & RM=NP2,Main            ,18706
655.9049
River Rch & RM=NP2,Main            ,14582.6
718.9306
River Rch & RM=NP2,Main            ,10453.4
785.3488
River Rch & RM=NP2,Main            ,10165.2
873.3489
River Rch & RM=NP2,Main            ,7088.8
962.6665
River Rch & RM=NP2,Main            ,6500.8
1034.388
River Rch & RM=NP2,Main            ,854.9
1148.422
Boundary for River Rch & Prof#=NP2,Main            , 1
Up Type= 0
Dn Type= 1
Dn Known WS=1534.79
DSS Import GetInterval= 0
DSS Import GetPeak= 0
DSS Import FillOption= 0

--- NP2.g01 (geometry) ---

Geom Title=USGS 10m DEM
Program Version=4.10

River Reach=NP2             ,Main
Reach XY= 30
     1907739.745      364959.662     1908423.525      365418.986
     1909088.288      365501.167     1909572.802      366073.519
     1909743.442      366011.468     1910062.313      366297.591
     1910921.369      366225.198     1911695.774      366669.955
     1912871.513      367000.955     1913515.466      367899.084
     1914009.389      368096.567     1914239.424      367801.428
     1914766.768      367688.581     1915382.219      366913.841
     1916371.803      366374.779     1916723.365      365823.564
     1916569.719      364866.966     1917391.334      364359.154
     1917232.913       364139.97     1917686.473      363599.605
     1919101.403      362805.334     1919600.535      362084.848
      1919801.49      362035.369     1920042.375      362267.574
      1920430.83      361898.651     1921003.747      361855.248
     1921132.653      361458.112     1920822.323      360909.067
     1921365.559       360335.04     1921573.892      360310.734

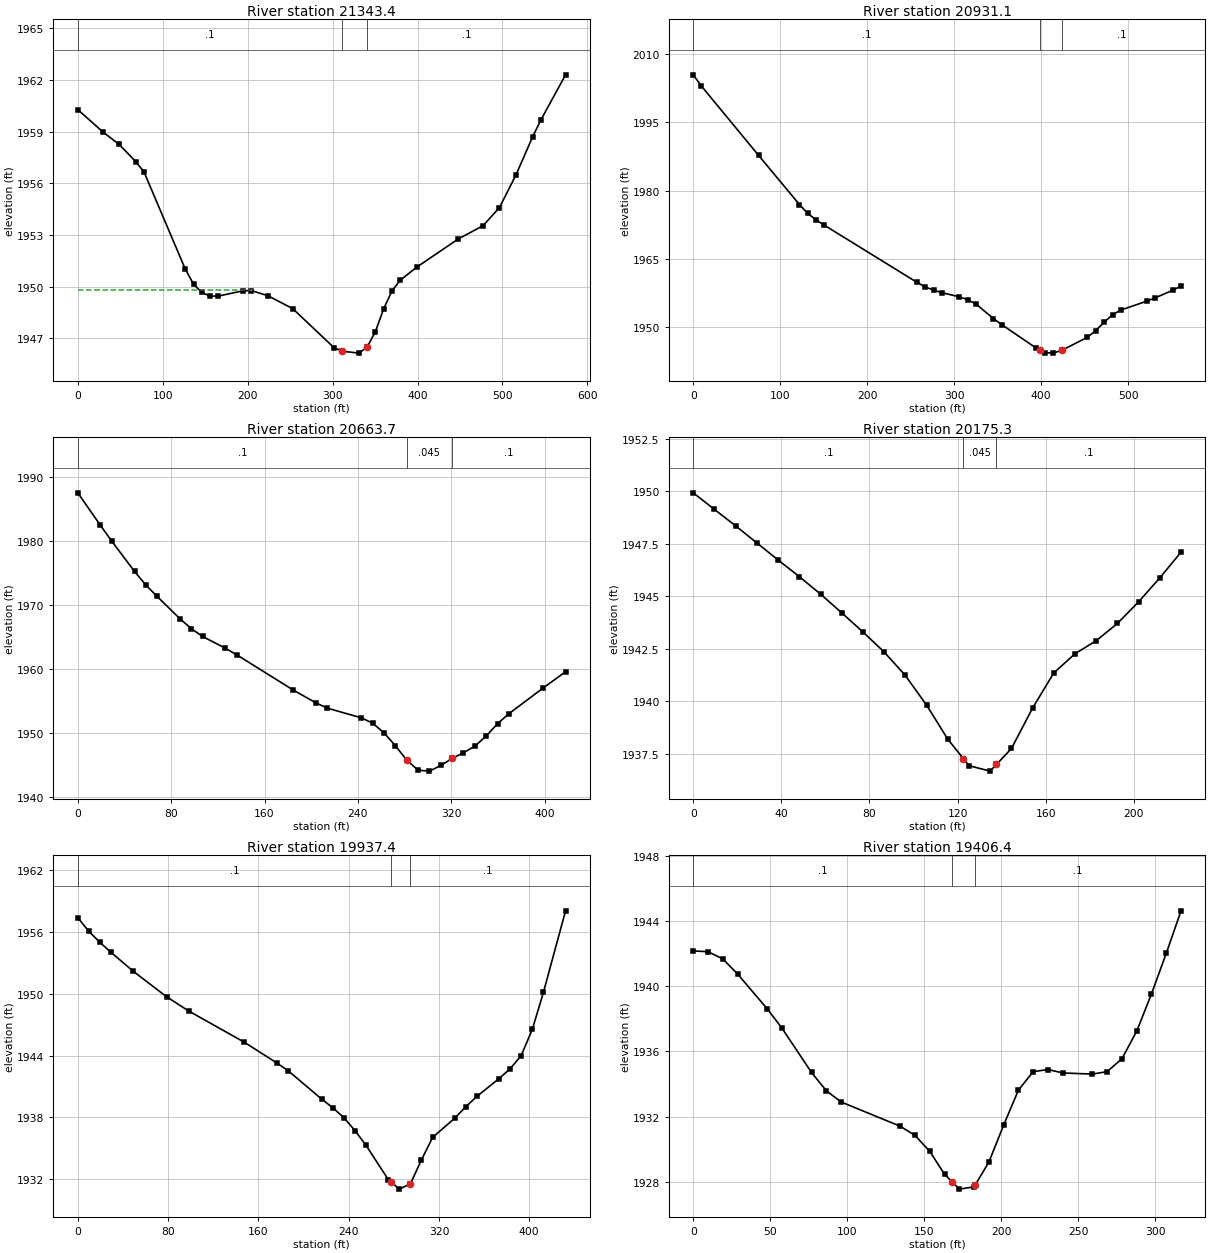
Type RM Length L Ch R = 1 ,21343.4 ,419.6,412.3,389.7
XS GIS Cut Line= 2
     1907548.638      365222.038     1907939.263      364801.031
#Sta/Elev= 30
       0 1960.27    29.2 1958.99    48.7 1958.25    68.1 1957.26    77.9 1956.66
   126.5 1951.02   136.3 1950.14     146 1949.66   155.8 1949.45   165.5 1949.45
   194.7 1949.76   204.4 1949.77   223.9 1949.47   253.1 1948.72   301.8 1946.45
   311.5 1946.25     331 1946.14   340.7 1946.49   350.4 1947.39   360.2 1948.72
   369.9 1949.75   379.6 1950.37   399.1 1951.13   447.8 1952.76     477 1953.53
   496.4 1954.58   515.9 1956.48   535.4 1958.68   545.1 1959.66   574.3 1962.29
#Mann= 3 , 0 , 0
       0      .1       0   311.5    .045       0   340.7      .1       0
#XS Ineff= 2 , 0
          205.35 1949.82
Permanent Ineff=
       F       F
Bank Sta=311.5,340.7
XS Rating Curve= 0 ,0
Exp/Cntr=0.3,0.1

Type RM Length L Ch R = 1 ,20931.1 ,269.3,267.3,265.8
XS GIS Cut Line= 3
     1907895.861      365595.302     1907908.881      365417.351
     1908078.152      365074.469
#Sta/Elev= 30
       0 2005.49     9.4 2003.01    75.1 1987.76   122.1 1976.94   131.5 1975.01
   140.9  1973.6   150.2 1972.45   256.9 1959.85   266.7 1958.82   276.5 1958.08
   286.3 1957.53   305.9 1956.63   315.7 1955.99   325.5 1954.98   345.1 1951.85
   354.9 1950.48   394.1 1945.37   398.2 1944.95   403.9 1944.36   413.7 1944.24
   423.6 1944.85     453 1947.71   462.8 1949.21   472.6 1951.09   482.4 1952.74
   492.2 1953.76   521.6 1955.69   531.4 1956.43     551 1958.06   560.8    1959
#Mann= 3 , 0 , 0
       0      .1       0   398.2    .045       0   423.6      .1       0
Bank Sta=398.2,423.6
XS Rating Curve= 0 ,0
Exp/Cntr=0.3,0.1

Type RM Length L Ch R = 1 ,20663.7 ,495.3,488.5,481.3
XS GIS Cut Line= 2
     1908129.368      365573.601     1908299.941       365192.09
#Sta/Elev= 30
       0 1987.58    19.4 1982.48    29.2 1979.99    48.6 1975.27    58.3 1973.15
      68 1971.35    87.5 1967.87    97.2 1966.32   106.9 1965.09   126.3 1963.26
   136.1 1962.23   184.7 1956.69   204.1 1954.69   213.8 1953.87     243 1952.35
   252.7 1951.51   262.4 1949.99   272.1 1947.99   281.81945.734   291.6 1944.15
   301.3 1944.01     311  1944.9   320.7 1945.99   330.4 1946.89   340.2 1947.92
   349.9  1949.5   359.6 1951.43   369.3 1952.99   398.5    1957   417.9 1959.57
#Mann= 3 , 0 , 0
       0      .1       0   281.8    .045       0   320.7      .1       0
Bank Sta=281.8,320.7
XS Rating Curve= 0 ,0
Exp/Cntr=0.3,0.1

Type RM Length L Ch R = 1 ,20175.3 ,236.3,237.8,239.4
XS GIS Cut Line= 2
     1908638.048      365551.899     1908646.729      365330.545
#Sta/Elev= 26
       0 1949.93     9.6 1949.14    19.3 1948.35    28.9 1947.54    38.5 1946.73
    48.2 1945.93    57.8  1945.1    67.4 1944.21      77  1943.3    86.7 1942.34
    96.3 1941.22     106  1939.8   115.6 1938.18   122.7 1937.25   125.2 1936.92
   134.8 1936.66   137.7 1936.98   144.5 1937.74   154.1 1939.67   163.7 1941.34
   173.4 1942.26     183 1942.88   192.6  1943.7   202.3 1944.74   211.9 1945.88
   221.5  1947.1
#Mann= 3 , 0 , 0
       0      .1       0   122.7    .045       0   137.7      .1       0
Bank Sta=122.7,137.7
XS Rating Curve= 0 ,0
Exp/Cntr=0.3,0.1

Type RM Length L Ch R = 1 ,19937.4 ,517.6,531,544.2
XS GIS Cut Line= 2
     1908842.909      365742.872     1908889.784      365313.184
#Sta/Elev= 30
       0 1957.36     9.8 1956.03    19.6 1954.96    29.5 1953.99    49.1 1952.17
    78.6  1949.7    98.2 1948.32   147.4  1945.3   176.8 1943.25   186.6 1942.51
   216.1 1939.78   225.9 1938.95   235.8 1937.98   245.6 1936.73   255.4  1935.3
   275.1 1931.99   277.9 1931.72   284.9 1931.06   294.7 1931.57   304.5 1933.89
   314.4 1936.07     334 1937.93   343.8 1939.04   353.6 1940.04   373.3 1941.77
   383.1 1942.72   392.9    1944   402.8 1946.56   412.6 1950.13   432.2 1958.02
#Mann= 3 , 0 , 0
       0      .1       0   277.9    .045       0   294.7      .1       0
Bank Sta=277.9,294.7
XS Rating Curve= 0 ,0
Exp/Cntr=0.3,0.1

Type RM Length L Ch R = 1 ,19406.4 ,175.3,175.9,176.3
XS GIS Cut Line= 2
     1909202.284      365829.677     1909410.618      365590.962
#Sta/Elev= 30
       0 1942.17     9.6 1942.12    19.2 1941.68    28.8 1940.75      48 1938.62
    57.6 1937.43    76.8 1934.71    86.4 1933.59      96  1932.9   134.4 1931.41
     144 1930.85   153.6 1929.87   163.2 1928.46   168.1    1928   172.8 1927.55
   182.4 1927.69   183.1  1927.8     192 1929.21   201.6 1931.48   211.2 1933.63
   220.8 1934.76   230.4 1934.89     240 1934.68   259.2 1934.61   268.8 1934.76
   278.4 1935.55     288 1937.24   297.6 1939.53   307.2 1942.02   316.8 1944.63
#Mann= 3 , 0 , 0
       0      .1       0   168.1    .045       0   183.1      .1       0
Bank Sta=168.1,183.1
XS Rating Curve= 0 ,0
Exp/Cntr=0.3,0.1

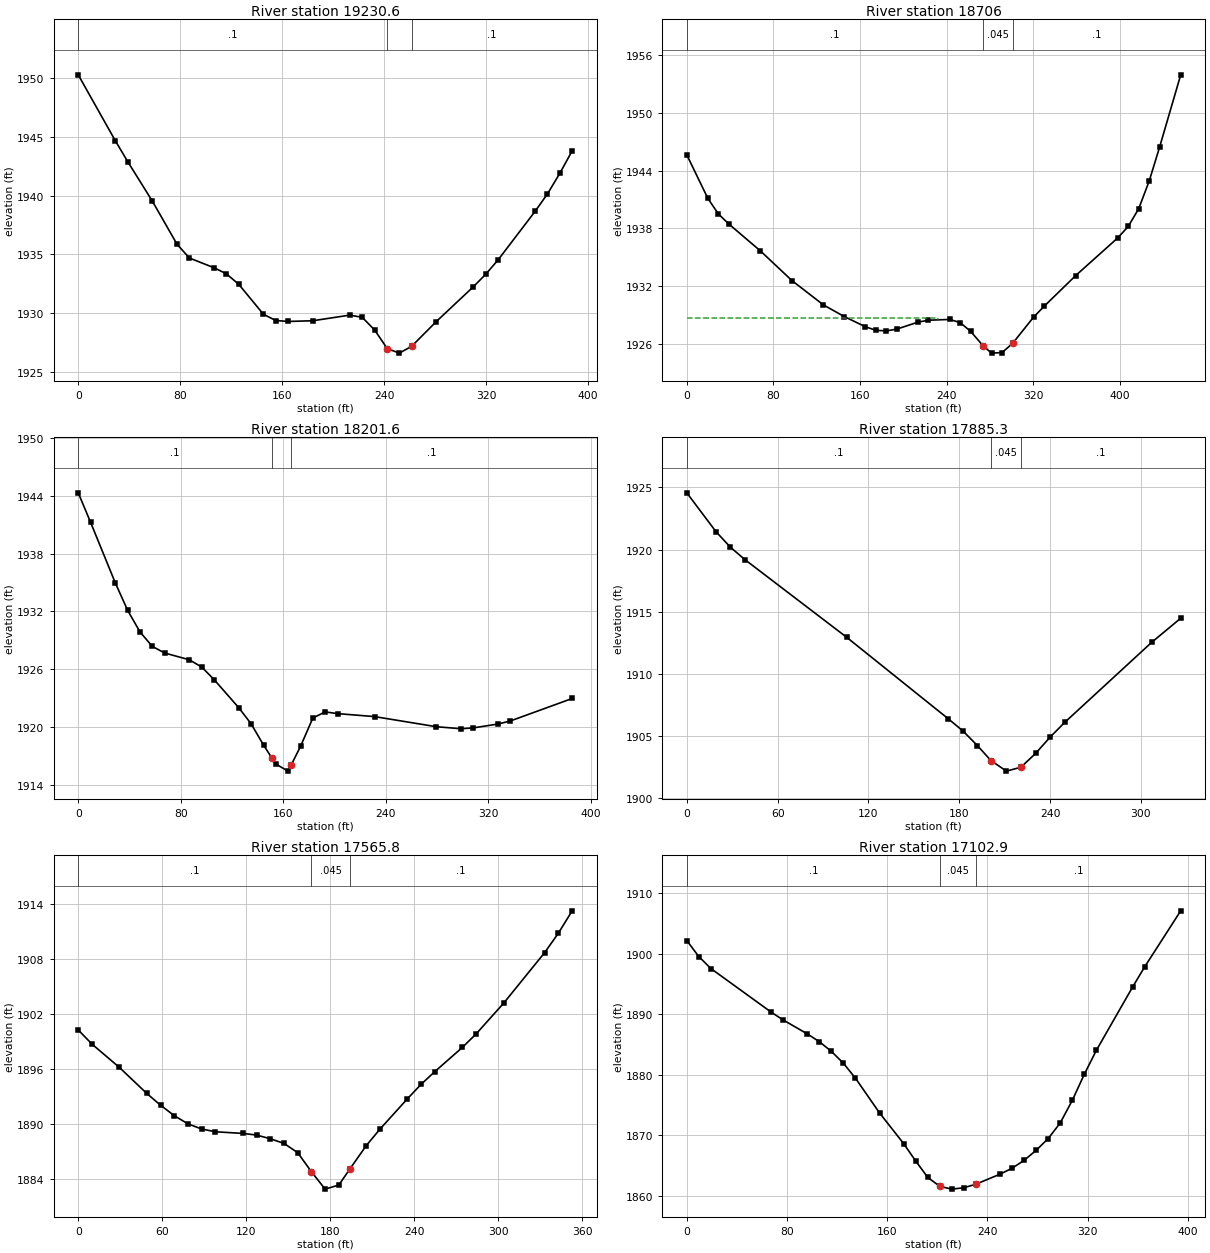
Type RM Length L Ch R = 1 ,19230.6 ,532.8,524.5,514.5
XS GIS Cut Line= 2
     1909267.388      366016.309     1909523.465       365725.51
#Sta/Elev= 27
       0 1950.26    29.1 1944.66    38.8 1942.89    58.1 1939.54    77.5 1935.87
    87.2  1934.7   106.6 1933.87   116.2 1933.36   125.9 1932.47   145.3 1929.92
     155 1929.39   164.7 1929.31     184 1929.37   213.1 1929.85   222.8 1929.66
   232.5 1928.59   242.4 1927.01   251.9 1926.62   261.6  1927.2   280.9  1929.3
     310 1932.26   319.7 1933.32   329.4 1934.54   358.4 1938.66   368.1 1940.14
   377.8 1941.89   387.5  1943.8
#Mann= 3 , 0 , 0
       0      .1       0   242.4    .045       0   261.6      .1       0
Bank Sta=242.4,261.6
XS Rating Curve= 0 ,0
Exp/Cntr=0.3,0.1

Type RM Length L Ch R = 1 ,18706   ,509.5,504.4,499.1
XS GIS Cut Line= 2
     1909675.375      366289.747     1909840.305      365864.399
#Sta/Elev= 30
       0 1945.64    19.4 1941.13    29.1 1939.51    38.8 1938.46      68 1935.66
    97.1 1932.58   126.2 1930.05   145.6 1928.83     165 1927.78   174.7 1927.41
   184.4 1927.35   194.1 1927.54   213.5 1928.26   223.2 1928.46   242.7 1928.54
   252.4 1928.22   262.1 1927.31   273.6 1925.81   281.5 1925.04   291.2  1925.1
   300.9 1926.05   320.3 1928.78     330  1929.9   359.1 1933.09     398 1937.01
   407.7  1938.2   417.4 1940.05   427.1 1942.93   436.8 1946.49   456.2 1953.96
#Mann= 3 , 0 , 0
       0      .1       0   273.6    .045       0   300.9      .1       0
#XS Ineff= 2 , 0
          232.39 1928.64
Permanent Ineff=
       F       F
Bank Sta=273.6,300.9
XS Rating Curve= 0 ,0
Exp/Cntr=0.3,0.1

Type RM Length L Ch R = 1 ,18201.6 ,325,316.3,307.5
XS GIS Cut Line= 2
     1910135.444      366472.038     1910187.527      366090.094
#Sta/Elev= 28
       0  1944.3     9.6 1941.25    28.9 1934.96    38.6 1932.09    48.2 1929.86
    57.8 1928.36    67.5 1927.67    86.7 1926.97    96.4 1926.21     106 1924.92
   125.3 1921.99   134.9 1920.33   144.6 1918.12   151.3 1916.74   154.2 1916.14
   163.8 1915.41   166.3 1916.07   173.5 1917.98   183.1 1920.92   192.7 1921.56
   202.4 1921.38   231.3 1921.07   279.5 1920.02   298.8 1919.81   308.4  1919.9
   327.7  1920.3   337.3 1920.62   385.5 1922.95
#Mann= 3 , 0 , 0
       0      .1       0   151.3    .045       0   166.3      .1       0
Bank Sta=151.3,166.3
XS Rating Curve= 0 ,0
Exp/Cntr=0.3,0.1

Type RM Length L Ch R = 1 ,17885.3 ,312,319.6,327
XS GIS Cut Line= 2
     1910504.368      366437.316     1910426.243      366120.476
#Sta/Elev= 16
       0 1924.57    19.2 1921.46    28.8  1920.2    38.4  1919.2   105.6 1912.96
   172.8  1906.4   182.4 1905.43     192 1904.25     201 1903.04   211.2  1902.2
   220.8 1902.52   230.4 1903.62     240 1904.93   249.6 1906.11   307.1 1912.55
   326.3 1914.49
#Mann= 3 , 0 , 0
       0      .1       0     201    .045       0   220.8      .1       0
Bank Sta=201,220.8
XS Rating Curve= 0 ,0
Exp/Cntr=0.3,0.1

Type RM Length L Ch R = 1 ,17565.8 ,455.2,462.8,470.5
XS GIS Cut Line= 2
     1910747.423      366411.274     1910777.805      366059.712
#Sta/Elev= 29
       0 1900.25     9.8 1898.71    29.4 1896.16      49 1893.32    58.8 1892.04
    68.6  1890.9    78.4    1890    88.2 1889.44      98 1889.14   117.6 1888.96
   127.4 1888.78   137.2 1888.38     147 1887.87   156.8 1886.86   166.6 1884.78
   176.4 1882.88   186.2 1883.33     194 1885.06   205.8 1887.63   215.6 1889.43
   235.2 1892.74     245 1894.32   254.8 1895.71   274.5 1898.35   284.3 1899.82
   303.9 1903.16   333.3  1908.7   343.1 1910.82   352.9 1913.25
#Mann= 3 , 0 , 0
       0      .1       0   166.6    .045       0     194      .1       0
Bank Sta=166.6,194
XS Rating Curve= 0 ,0
Exp/Cntr=0.3,0.1

Type RM Length L Ch R = 1 ,17102.9 ,725.4,722.2,719
XS GIS Cut Line= 2
     1911107.666      366554.503     1911268.256       366194.26
#Sta/Elev= 30
       0 1902.19     9.6 1899.54    19.2 1897.57    67.3 1890.37      77 1889.06
    96.2 1886.77   105.8 1885.48   115.4 1883.89   125.1 1881.91   134.7 1879.44
   153.9 1873.71   173.2 1868.63   182.8 1865.76   192.4 1863.06     202 1861.58
   211.6 1861.12   221.3 1861.35   230.9 1861.94   250.1 1863.59   259.7 1864.57
   269.4 1865.88     279 1867.54   288.6 1869.48   298.2 1872.06   307.8 1875.78
   317.5 1880.13   327.1 1884.08   355.9 1894.48   365.6 1897.84   394.4  1907.1
#Mann= 3 , 0 , 0
       0      .1       0     202    .045       0   230.9      .1       0
Bank Sta=202,230.9
XS Rating Curve= 0 ,0
Exp/Cntr=0.3,0.1

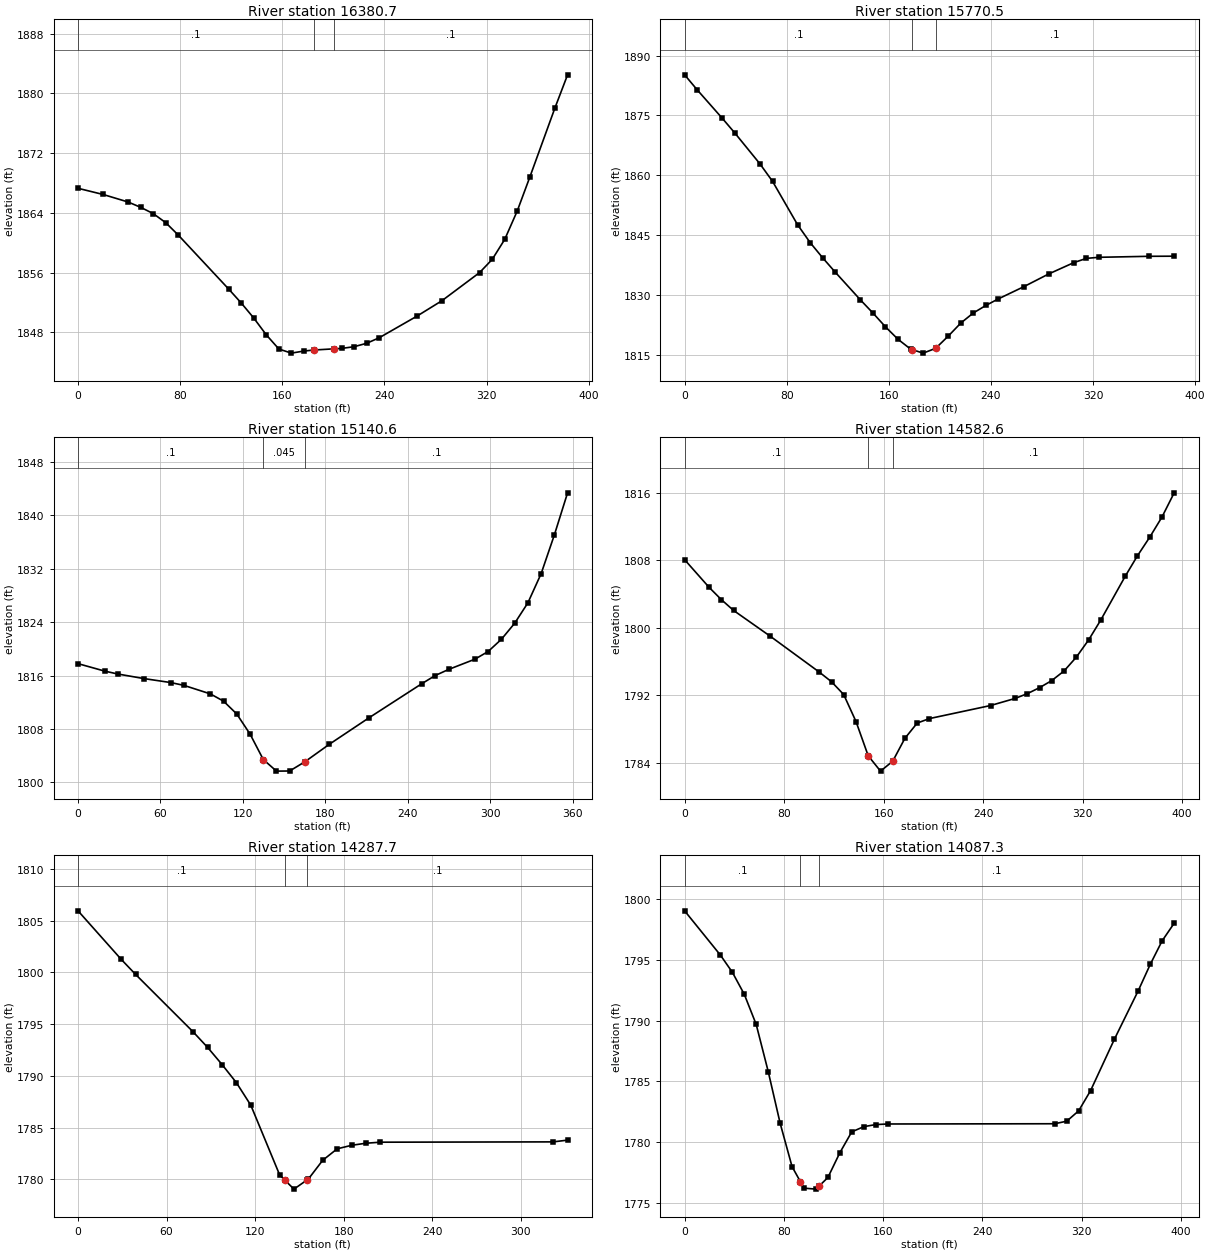
Type RM Length L Ch R = 1 ,16380.7 ,607.9,610.3,612.6
XS GIS Cut Line= 2
     1911771.729      366867.003     1911875.895       366498.08
#Sta/Elev= 29
       0  1867.3    19.7 1866.47    39.3 1865.46    49.2 1864.74      59  1863.9
    68.8 1862.68    78.6 1861.02     118  1853.8   127.8 1851.94   137.6 1849.93
   147.4 1847.68   157.3 1845.77   167.1 1845.22   176.9  1845.5   185.1 1845.64
   200.1 1845.79   206.4 1845.85   216.2 1846.08   226.1 1846.54   235.9 1847.28
   265.4 1850.17     285 1852.24   314.5 1856.01   324.4 1857.78   334.2 1860.46
     344 1864.27   353.9 1868.83   373.5 1878.06   383.4  1882.5
#Mann= 3 , 0 , 0
       0      .1       0   185.1    .045       0   200.1      .1       0
Bank Sta=185.1,200.1
XS Rating Curve= 0 ,0
Exp/Cntr=0.3,0.1

Type RM Length L Ch R = 1 ,15770.5 ,616.3,629.9,663.5
XS GIS Cut Line= 2
     1912309.923      367092.698     1912453.152      366736.795
#Sta/Elev= 30
       0 1885.17     9.8 1881.43    29.5 1874.29    39.4 1870.58      59 1862.88
    68.9 1858.49    88.5 1847.63    98.4 1843.14   108.2 1839.33     118 1835.76
   137.7 1828.82   147.6  1825.5   157.4 1822.05   167.2 1818.94   177.1 1816.47
   178.3 1816.35   186.9 1815.47   196.7 1816.67   206.6 1819.74   216.4    1823
   226.2 1825.52   236.1 1827.42   245.9 1829.07   265.6 1832.08   285.3  1835.3
     305 1838.14   314.8  1839.2   324.6 1839.47     364 1839.72   383.6 1839.75
#Mann= 3 , 0 , 0
       0      .1       0   178.3    .045       0   196.7      .1       0
Bank Sta=178.3,196.7
XS Rating Curve= 0 ,0
Exp/Cntr=0.3,0.1

Type RM Length L Ch R = 1 ,15140.6 ,552,558,562.7
XS GIS Cut Line= 2
     1912822.076      367175.163     1913065.131      366914.747
#Sta/Elev= 27
       0 1817.78    19.3 1816.67    28.9 1816.23    48.1 1815.54    67.4 1814.95
      77 1814.53    96.3 1813.25   105.9 1812.16   115.5 1810.24   125.2 1807.22
   134.8 1803.42   144.4 1801.68     154  1801.7   165.2  1803.1   182.9 1805.71
   211.8 1809.68   250.3  1814.8   259.9    1816   269.6 1816.91   288.8 1818.45
   298.4  1819.6   308.1 1821.44   317.7 1823.83   327.3 1826.88     337 1831.28
   346.6 1837.07   356.2 1843.37
#Mann= 3 , 0 , 0
       0      .1       0   134.8    .045       0   165.2      .1       0
Bank Sta=134.8,165.2
XS Rating Curve= 0 ,0
Exp/Cntr=0.3,0.1

Type RM Length L Ch R = 1 ,14582.6 ,298.6,294.9,325.9
XS GIS Cut Line= 2
     1913086.833       367596.17     1913412.354      367374.816
#Sta/Elev= 29
       0 1808.09    19.7 1804.81    29.5 1803.36    39.4 1802.07    68.9 1799.01
   108.2 1794.77   118.1 1793.62   127.9  1792.1   137.8  1788.9   147.6 1784.84
   157.5 1783.02   167.3 1784.19   177.1 1786.91     187 1788.72   196.8 1789.25
     246  1790.8   265.7 1791.64   275.6 1792.21   285.4 1792.92   295.2 1793.76
   305.1  1794.9   314.9 1796.53   324.8 1798.57   334.6 1800.94   354.3 1806.14
   364.1 1808.56     374 1810.77   383.8 1813.15   393.6 1816.02
#Mann= 3 , 0 , 0
       0      .1       0   147.6    .045       0   167.3      .1       0
Bank Sta=147.6,167.3
XS Rating Curve= 0 ,0
Exp/Cntr=0.3,0.1

Type RM Length L Ch R = 1 ,14287.7 ,210.8,200.4,197.9
XS GIS Cut Line= 2
     1913277.805      367843.566     1913520.861      367617.872
#Sta/Elev= 20
       0 1805.96    29.3 1801.26      39 1799.81      78 1794.25    87.8 1792.75
    97.6 1791.09   107.3 1789.34   117.1 1787.15   136.6 1780.42   140.3 1779.89
   146.3 1779.04   155.3 1779.94   156.1 1780.02   165.8 1781.83   175.6 1782.94
   185.4 1783.28   195.1 1783.48   204.9 1783.58   321.9 1783.61   331.7 1783.78
#Mann= 3 , 0 , 0
       0      .1       0   140.3    .045       0   155.3      .1       0
Bank Sta=140.3,155.3
XS Rating Curve= 0 ,0
Exp/Cntr=0.3,0.1

Type RM Length L Ch R = 1 ,14087.3 ,203.5,198,192.1
XS GIS Cut Line= 2
     1913442.736      367965.094     1913694.472      367661.274
#Sta/Elev= 27
       0 1799.04    28.9 1795.39    38.5 1793.98    48.1 1792.17    57.7 1789.69
    67.4 1785.81      77 1781.56    86.6 1777.99    93.4 1776.74    96.2 1776.22
   105.9 1776.14   108.4 1776.39   115.5  1777.1   125.1 1779.13   134.7 1780.85
   144.4 1781.28     154 1781.45   163.6  1781.5   298.3 1781.52     308 1781.73
   317.6 1782.58   327.2 1784.24   346.4 1788.47   365.7 1792.48   375.3 1794.63
   384.9 1796.57   394.6 1798.02
#Mann= 3 , 0 , 0
       0      .1       0    93.4    .045       0   108.4      .1       0
Bank Sta=93.4,108.4
XS Rating Curve= 0 ,0
Exp/Cntr=0.3,0.1

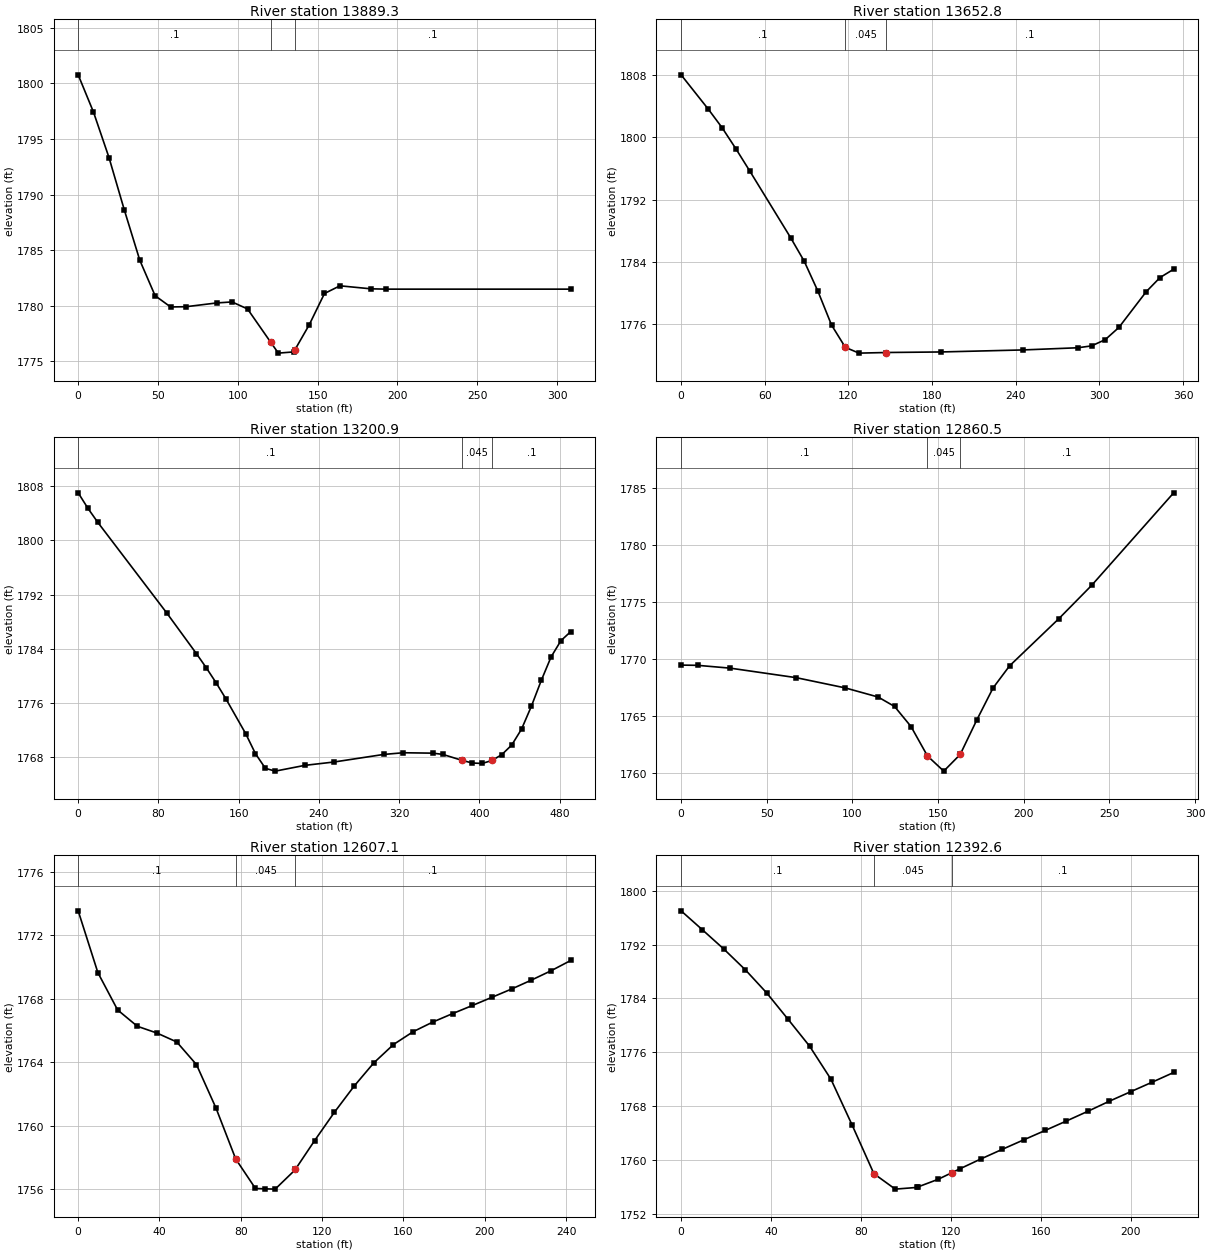
Type RM Length L Ch R = 1 ,13889.3 ,236.3,236.5,236.6
XS GIS Cut Line= 2
     1913633.708      368051.899     1913768.256      367774.122
#Sta/Elev= 21
       0 1800.76     9.6 1797.41    19.3 1793.33    28.9 1788.62    38.6  1784.1
    48.2 1780.91    57.9  1779.9    67.5 1779.92    86.8 1780.26    96.4 1780.35
   106.1 1779.72   120.7 1776.71   125.4 1775.75     135 1775.86   135.7 1776.03
   144.7 1778.28   154.3 1781.11     164  1781.8   183.3 1781.53   192.9  1781.5
   308.6  1781.5
#Mann= 3 , 0 , 0
       0      .1       0   120.7    .045       0   135.7      .1       0
Bank Sta=120.7,135.7
XS Rating Curve= 0 ,0
Exp/Cntr=0.3,0.1

Type RM Length L Ch R = 1 ,13652.8 ,473.6,451.9,429.5
XS GIS Cut Line= 2
      1913829.02      368169.087      1913985.27      367852.247
#Sta/Elev= 21
       0 1808.04    19.6 1803.61    29.4 1801.25    39.2 1798.57    49.1 1795.73
    78.5 1787.14    88.3  1784.1    98.1 1780.26   107.9  1775.9   117.8 1773.03
   127.6 1772.29   147.2 1772.37   186.4 1772.44   245.3  1772.7   284.6 1772.98
   294.4 1773.22   304.2 1774.02     314 1775.59   333.6 1780.18   343.5    1782
   353.3 1783.07
#Mann= 3 , 0 , 0
       0      .1       0   117.8    .045       0   147.2      .1       0
Bank Sta=117.8,147.2
XS Rating Curve= 0 ,0
Exp/Cntr=0.3,0.1

Type RM Length L Ch R = 1 ,13200.9 ,339.6,340.3,331.9
XS GIS Cut Line= 2
     1914315.131       368216.83     1914085.097      367782.802
#Sta/Elev= 30
       0    1807     9.8  1804.7    19.6 1802.64    88.4 1789.27   117.9 1783.29
   127.7 1781.21   137.5    1779   147.4  1776.6     167  1771.5   176.8 1768.53
   186.7 1766.37   196.5 1765.96     226 1766.81   255.4 1767.31   304.6 1768.42
   324.2 1768.67   353.7 1768.61   363.5 1768.43   383.2 1767.53     393 1767.16
   402.8 1767.09   412.6 1767.53   422.4 1768.39   432.3  1769.8   442.1 1772.15
   451.9 1775.52   461.8 1779.34   471.6 1782.81   481.4  1785.2   491.2 1786.54
#Mann= 3 , 0 , 0
       0      .1       0   383.2    .045       0   412.6      .1       0
Bank Sta=383.2,412.6
XS Rating Curve= 0 ,0
Exp/Cntr=0.3,0.1

Type RM Length L Ch R = 1 ,12860.5 ,249.2,253.5,265
XS GIS Cut Line= 2
     1914475.722      367960.753     1914336.833      367709.017
#Sta/Elev= 17
       0 1769.48     9.6 1769.46    28.8 1769.21    67.1 1768.38    95.8 1767.48
     115 1766.68   124.6 1765.85   134.2 1764.09   143.8 1761.51   153.3 1760.18
   162.9 1761.64   172.5 1764.64   182.1 1767.48   191.7 1769.41   220.4 1773.54
   239.6 1776.47   287.5 1784.59
#Mann= 3 , 0 , 0
       0      .1       0   143.8    .045       0   162.9      .1       0
Bank Sta=143.8,162.9
XS Rating Curve= 0 ,0
Exp/Cntr=0.3,0.1

Type RM Length L Ch R = 1 ,12607.1 ,225.7,214.5,203.1
XS GIS Cut Line= 2
     1914684.055      367863.097      1914601.59      367635.233
#Sta/Elev= 28
       0 1773.55     9.7 1769.65    19.4  1767.3    29.1 1766.27    38.8 1765.84
    48.5 1765.28    58.2 1763.85    67.8 1761.11    77.5  1757.9    87.2 1756.04
    91.8 1756.02    96.9    1756   106.6  1757.2   106.8 1757.24   116.3 1759.06
     126 1760.84   135.7 1762.49   145.4 1763.96   155.1 1765.12   164.8 1765.93
   174.5 1766.54   184.2 1767.07   193.9 1767.58   203.6  1768.1   213.2 1768.62
   222.9 1769.18   232.6 1769.77   242.3 1770.42
#Mann= 3 , 0 , 0
       0      .1       0    77.5    .045       0   106.8      .1       0
Bank Sta=77.5,106.8
XS Rating Curve= 0 ,0
Exp/Cntr=0.3,0.1

Type RM Length L Ch R = 1 ,12392.6 ,646.5,646.5,646.1
XS GIS Cut Line= 2
     1914890.956      367701.693     1914724.289      367559.331
#Sta/Elev= 26
       0    1797     9.5 1794.18    19.1  1791.3    28.6 1788.24    38.1 1784.81
    47.6  1780.9    57.2  1776.9    66.7 1771.99    76.2 1765.13    85.8 1757.97
    95.3 1755.68   104.8 1755.93   105.5 1756.02   114.4 1757.14   120.5 1758.12
   123.9 1758.67   133.4 1760.16     143  1761.6   152.5    1763     162 1764.39
   171.5  1765.8   181.1 1767.25   190.6 1768.74   200.1 1770.15   209.7 1771.57
   219.2    1773
#Mann= 3 , 0 , 0
       0      .1       0    85.8    .045       0   120.5      .1       0
Bank Sta=85.8,120.5
XS Rating Curve= 0 ,0
Exp/Cntr=0.3,0.1

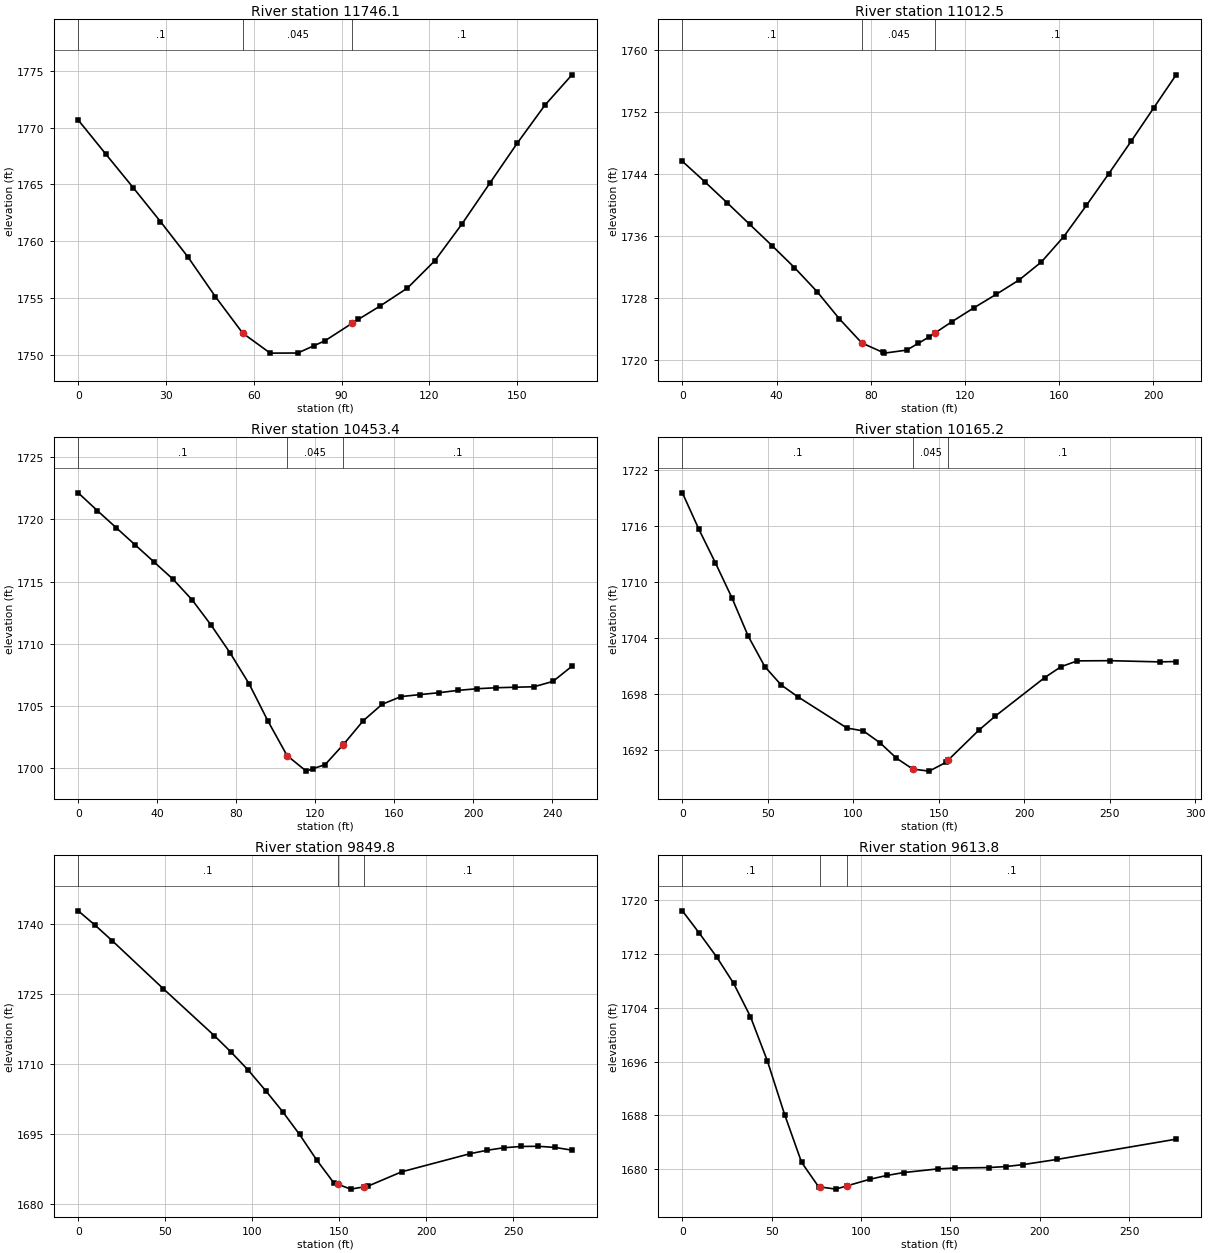
Type RM Length L Ch R = 1 ,11746.1 ,724.8,733.6,742.5
XS GIS Cut Line= 2
      1915264.22      367186.068     1915135.747      367076.693
#Sta/Elev= 21
       0 1770.66     9.4 1767.67    18.8  1764.7    28.1 1761.72    37.5  1758.6
    46.9  1755.1    56.2  1751.9    65.6 1750.14      75 1750.15    80.7 1750.81
    84.4 1751.24    93.7 1752.79    95.7 1753.11   103.1 1754.28   112.5 1755.87
   121.9 1758.29   131.2 1761.54   140.6 1765.09     150 1768.62   159.4 1771.95
   168.7 1774.64
#Mann= 3 , 0 , 0
       0      .1       0    56.2    .045       0    93.7      .1       0
Bank Sta=56.2,93.7
XS Rating Curve= 0 ,0
Exp/Cntr=0.3,0.1

Type RM Length L Ch R = 1 ,11012.5 ,555.9,559,562.2
XS GIS Cut Line= 2
     1915805.308      366765.929     1915708.085      366580.165
#Sta/Elev= 26
       0 1745.64     9.5 1743.01    19.1 1740.27    28.6 1737.51    38.1 1734.76
    47.6 1731.94    57.2 1728.84    66.7 1725.32    76.2 1722.22    85.1 1721.01
    85.8 1720.91    95.3  1721.3   100.1 1722.16   104.8    1723   107.51723.548
   114.4 1724.95   123.9 1726.77   133.4 1728.51     143 1730.34   152.5 1732.67
     162 1735.94   171.6 1739.96   181.1 1744.05   190.6 1748.23   200.1 1752.49
   209.7 1756.79
#Mann= 3 , 0 , 0
       0      .1       0    76.2    .045       0   107.5      .1       0
Bank Sta=76.2,107.5
XS Rating Curve= 0 ,0
Exp/Cntr=0.3,0.1

Type RM Length L Ch R = 1 ,10453.4 ,304.9,288.2,271.4
XS GIS Cut Line= 2
     1916289.683      366538.498     1916202.877      366304.123
#Sta/Elev= 29
       0 1722.14     9.6 1720.72    19.2 1719.34    28.8 1717.96    38.4 1716.58
    48.1 1715.18    57.7 1713.53    67.3  1711.5    76.9 1709.27    86.5 1706.79
    96.1 1703.78   105.7 1701.03   115.4 1699.78     119 1699.98     125 1700.31
     134 1701.88   134.6 1701.99   144.2 1703.82   153.8 1705.15   163.4 1705.77
     173 1705.93   182.6 1706.08   192.3 1706.27   201.9  1706.4   211.5 1706.48
   221.1 1706.52   230.7 1706.56   240.3 1706.99   249.9 1708.21
#Mann= 3 , 0 , 0
       0      .1       0   105.7    .045       0     134      .1       0
Bank Sta=105.7,134
XS Rating Curve= 0 ,0
Exp/Cntr=0.3,0.1

Type RM Length L Ch R = 1 ,10165.2 ,314.3,315.4,316.8
XS GIS Cut Line= 2
     1916563.988      366305.859      1916308.78      366170.443
#Sta/Elev= 24
       0  1719.6     9.6  1715.7    19.3 1712.08    28.9 1708.35    38.5  1704.2
    48.2 1700.93    57.8 1698.95    67.4  1697.7    96.3 1694.32   105.9 1694.01
   115.6 1692.74   125.2 1691.09   134.8 1689.91   144.4 1689.69   154.1 1690.62
   155.7 1690.91   173.4 1694.08     183 1695.59   211.9 1699.73   221.5 1700.91
   231.1 1701.54   250.4 1701.56   279.3 1701.43   288.9 1701.47
#Mann= 3 , 0 , 0
       0      .1       0   134.8    .045       0   155.7      .1       0
Bank Sta=134.8,155.7
XS Rating Curve= 0 ,0
Exp/Cntr=0.3,0.1

Type RM Length L Ch R = 1 ,9849.8  ,248,236,223.7
XS GIS Cut Line= 2
     1916739.335      366074.956     1916501.488      365920.443
#Sta/Elev= 24
       0 1742.71     9.8  1739.6    19.6  1736.3    48.9 1726.06    78.2 1716.04
      88 1712.46    97.8 1708.62   107.6 1704.33   117.4 1699.83   127.1 1694.96
   136.9 1689.53   146.7 1684.66   149.3 1684.29   156.5 1683.27   164.3 1683.76
   166.3 1683.89   185.8 1686.97     225 1690.83   234.7 1691.56   244.5 1692.11
   254.3 1692.38   264.1 1692.42   273.8 1692.18   283.6 1691.59
#Mann= 3 , 0 , 0
       0      .1       0   149.3    .045       0   164.3      .1       0
Bank Sta=149.3,164.3
XS Rating Curve= 0 ,0
Exp/Cntr=0.3,0.1

Type RM Length L Ch R = 1 ,9613.8  ,292.2,285,277.7
XS GIS Cut Line= 2
     1916807.044      365802.387     1916531.002      365790.234
#Sta/Elev= 22
       0 1718.44     9.5  1715.1    19.1  1711.6    28.6 1707.67    38.1 1702.67
    47.6 1696.06    57.2 1688.11    66.7 1680.99    76.2 1677.36      77 1677.33
    85.8    1677      92 1677.48   104.8 1678.46   114.3 1679.03   123.9 1679.47
   142.9 1680.01   152.4 1680.14   171.5 1680.21     181 1680.36   190.6 1680.65
   209.6 1681.42   276.3 1684.44
#Mann= 3 , 0 , 0
       0      .1       0      77    .045       0      92      .1       0
Bank Sta=77,92
XS Rating Curve= 0 ,0
Exp/Cntr=0.3,0.1

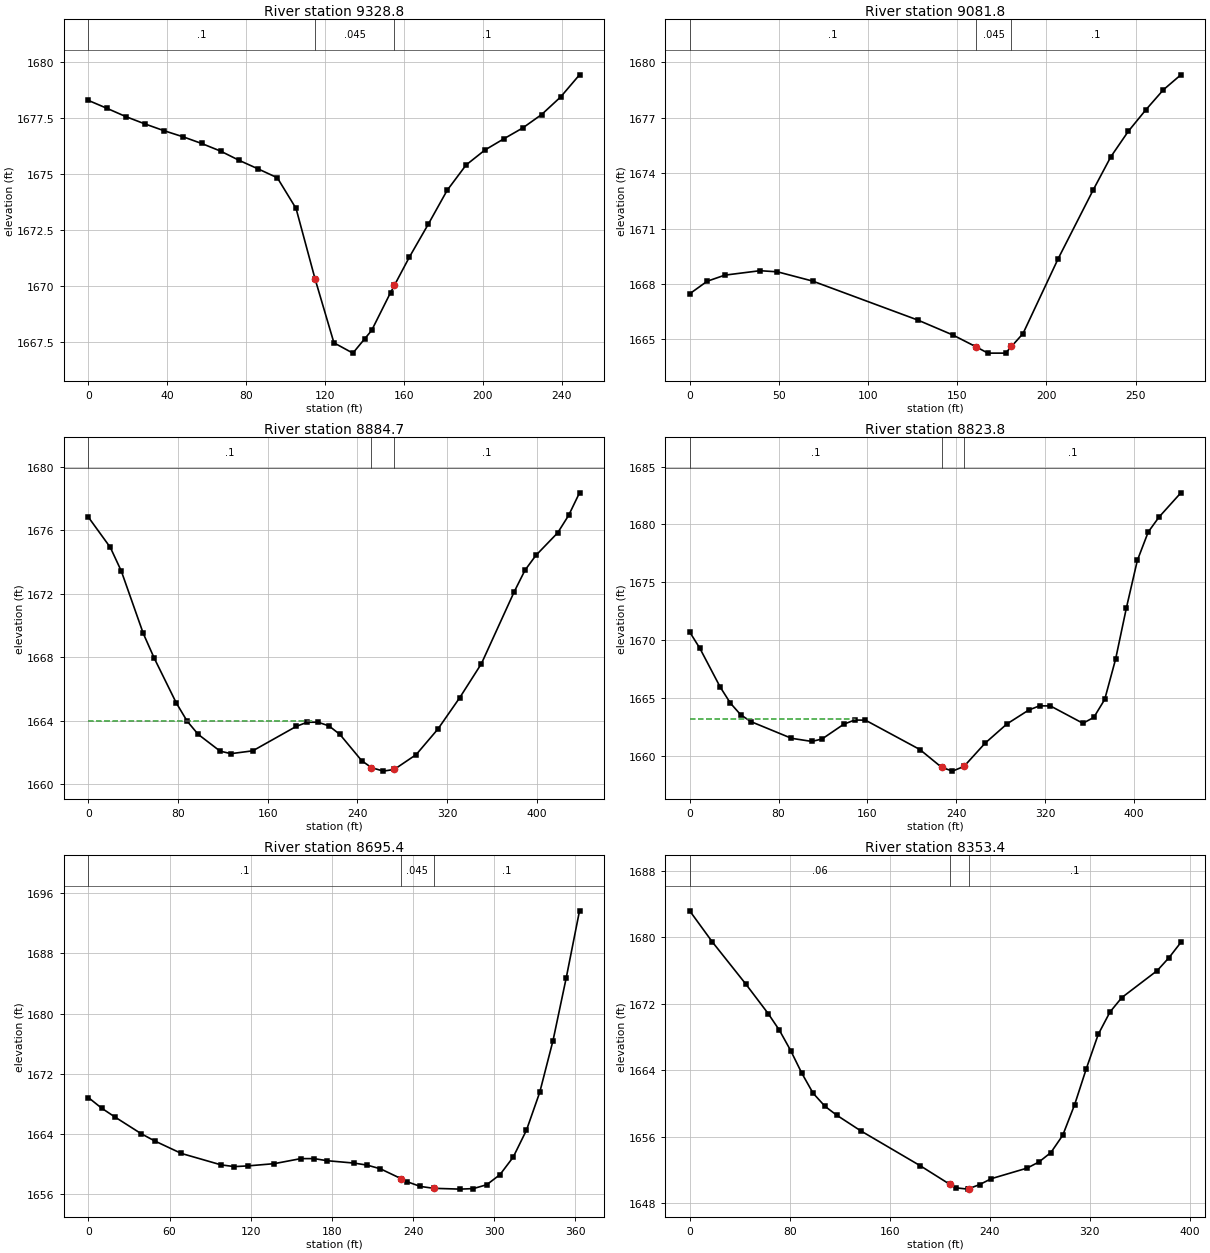
Type RM Length L Ch R = 1 ,9328.8  ,247.1,247,246.8
XS GIS Cut Line= 2
     1916782.738      365488.151     1916543.155      365555.859
#Sta/Elev= 29
       0 1678.27     9.6 1677.91    19.2 1677.54    28.7 1677.22    38.3 1676.92
    47.9 1676.65    57.4 1676.35      67 1676.01    76.6 1675.59    86.2 1675.21
    95.8 1674.82   105.3 1673.45   114.9 1670.32   124.5 1667.46   134.1    1667
   140.2 1667.65   143.6 1668.01   153.2  1669.7   155.2 1670.03   162.8 1671.29
   172.4 1672.76   181.9 1674.26   191.5 1675.39   201.1 1676.06   210.7 1676.56
   220.2 1677.04   229.8 1677.64   239.4 1678.42     249 1679.41
#Mann= 3 , 0 , 0
       0      .1       0   114.9    .045       0   155.2      .1       0
Bank Sta=114.9,155.2
XS Rating Curve= 0 ,0
Exp/Cntr=0.3,0.1

Type RM Length L Ch R = 1 ,9081.8  ,207.9,197.2,176.9
XS GIS Cut Line= 2
     1916735.863       365252.04     1916470.238      365324.956
#Sta/Elev= 20
       0 1667.47     9.8 1668.15    19.7 1668.48    39.4 1668.72    49.2 1668.66
    68.9 1668.16   127.9 1666.05   147.6 1665.24   160.4 1664.61   167.2 1664.26
   177.1 1664.26  180.421664.619   186.9 1665.32   206.6 1669.37   226.3  1673.1
   236.1 1674.88   245.9 1676.26   255.8 1677.43   265.6 1678.51   275.4 1679.32
#Mann= 3 , 0 , 0
       0      .1       0   160.4    .045       0  180.42      .1       0
Bank Sta=160.4,180.42
XS Rating Curve= 0 ,0
Exp/Cntr=0.3,0.1

Type RM Length L Ch R = 1 ,8884.7  ,57.7,60.9,73.6
XS GIS Cut Line= 3
     1916815.566      365065.788     1916701.892      365035.968
     1916431.465      365208.058
#Sta/Elev= 30
       0 1676.82    19.6 1674.91    29.4 1673.42      49 1669.49    58.8 1667.93
    78.4 1665.12    88.1 1663.97    97.9 1663.14   117.5 1662.08   127.2 1661.92
   146.7  1662.1   185.5 1663.64   195.2  1663.9   204.9  1663.9   214.6 1663.67
   224.4 1663.13   243.8 1661.48   252.5 1661.04   263.2 1660.82   272.9 1660.93
   292.4 1661.86   311.8 1663.47   331.2 1665.44   350.6 1667.59   379.8 1672.11
   389.5 1673.48   399.2 1674.41   418.6 1675.83   428.4 1676.93   438.1 1678.35
#Mann= 3 , 0 , 0
       0      .1       0   252.5    .045       0   272.9      .1       0
#XS Ineff= 2 , 0
           200.7 1663.97
Permanent Ineff=
       F       F
Bank Sta=252.5,272.9
XS Rating Curve= 0 ,0
Exp/Cntr=0.3,0.1

Type RM Length L Ch R = 1 ,8823.8  ,108,128.4,148.7
XS GIS Cut Line= 3
     1916794.732      365022.819     1916679.862      364991.118
      1916407.16      365164.656
#Sta/Elev= 30
       0 1670.69     9.2 1669.27    27.5 1665.92    36.7 1664.53    45.8 1663.54
      55 1662.94    91.7 1661.49     110 1661.22   119.2 1661.43   138.8 1662.71
   148.6 1663.07   158.3 1663.06   207.3 1660.52   226.9 1658.98   236.7 1658.65
   247.1 1659.06   266.1 1661.07   285.7 1662.73   305.3 1663.93   315.1  1664.3
   324.9 1664.29   354.2 1662.79     364  1663.3   373.8 1664.85   383.6 1668.33
   393.4  1672.8   403.2 1676.88     413 1679.34   422.8 1680.64   442.4 1682.73
#Mann= 3 , 0 , 0
       0      .1       0   226.9    .045       0   247.1      .1       0
#XS Ineff= 2 , 0
          148.59 1663.15
Permanent Ineff=
       F       F
Bank Sta=226.9,247.1
XS Rating Curve= 0 ,0
Exp/Cntr=0.3,0.1

Type RM Length L Ch R = 1 ,8695.4  ,321.5,342,362.5
XS GIS Cut Line= 2
     1916806.451      365003.288     1916459.243      364897.294
#Sta/Elev= 30
       0 1668.87     9.8 1667.46    19.6 1666.29    39.2 1664.05    49.1  1663.1
    68.7 1661.45    98.1 1659.93   107.9  1659.7   117.7 1659.79   137.4 1660.09
     157 1660.76   166.8 1660.76   176.6 1660.48   196.2 1660.17     206  1659.9
   215.8 1659.41   230.9 1658.12   235.5  1657.7   245.3 1657.07   255.1 1656.82
   274.7 1656.71   284.5 1656.78   294.4 1657.29   304.2 1658.63     314 1660.96
   323.8 1664.54   333.6 1669.56   343.4 1676.42   353.2 1684.77     363 1693.65
#Mann= 3 , 0 , 0
       0      .1       0   230.9    .045       0   255.1      .1       0
Bank Sta=230.9,255.1
XS Rating Curve= 0 ,0
Exp/Cntr=0.3,0.1

Type RM Length L Ch R = 1 ,8353.4  ,213.5,208.5,200.1
XS GIS Cut Line= 4
     1916926.257      364977.156     1916861.444      364902.707
     1916794.818      364714.316     1916724.868      364650.767
#Sta/Elev= 30
       0 1683.16      18 1679.44    44.9 1674.35    62.8  1670.8    71.8 1668.79
    80.8 1666.35    89.7 1663.63    98.7 1661.23   108.2 1659.65   117.7 1658.57
   136.8  1656.7   184.4  1652.5   208.2 1650.25   212.9 1649.84   222.4 1649.68
   223.2 1649.73   231.9 1650.22   241.4 1650.94     270 1652.21   279.5 1652.95
     289 1654.08   298.5 1656.16     308 1659.84   317.4 1664.19   326.9  1668.3
   336.3 1670.99   345.8 1672.73   374.1 1675.97   383.6 1677.54     393 1679.36
#Mann= 3 , 0 , 0
       0     .06       0   208.2    .045       0   223.2      .1       0
Bank Sta=208.2,223.2
XS Rating Curve= 0 ,0
Exp/Cntr=0.3,0.1