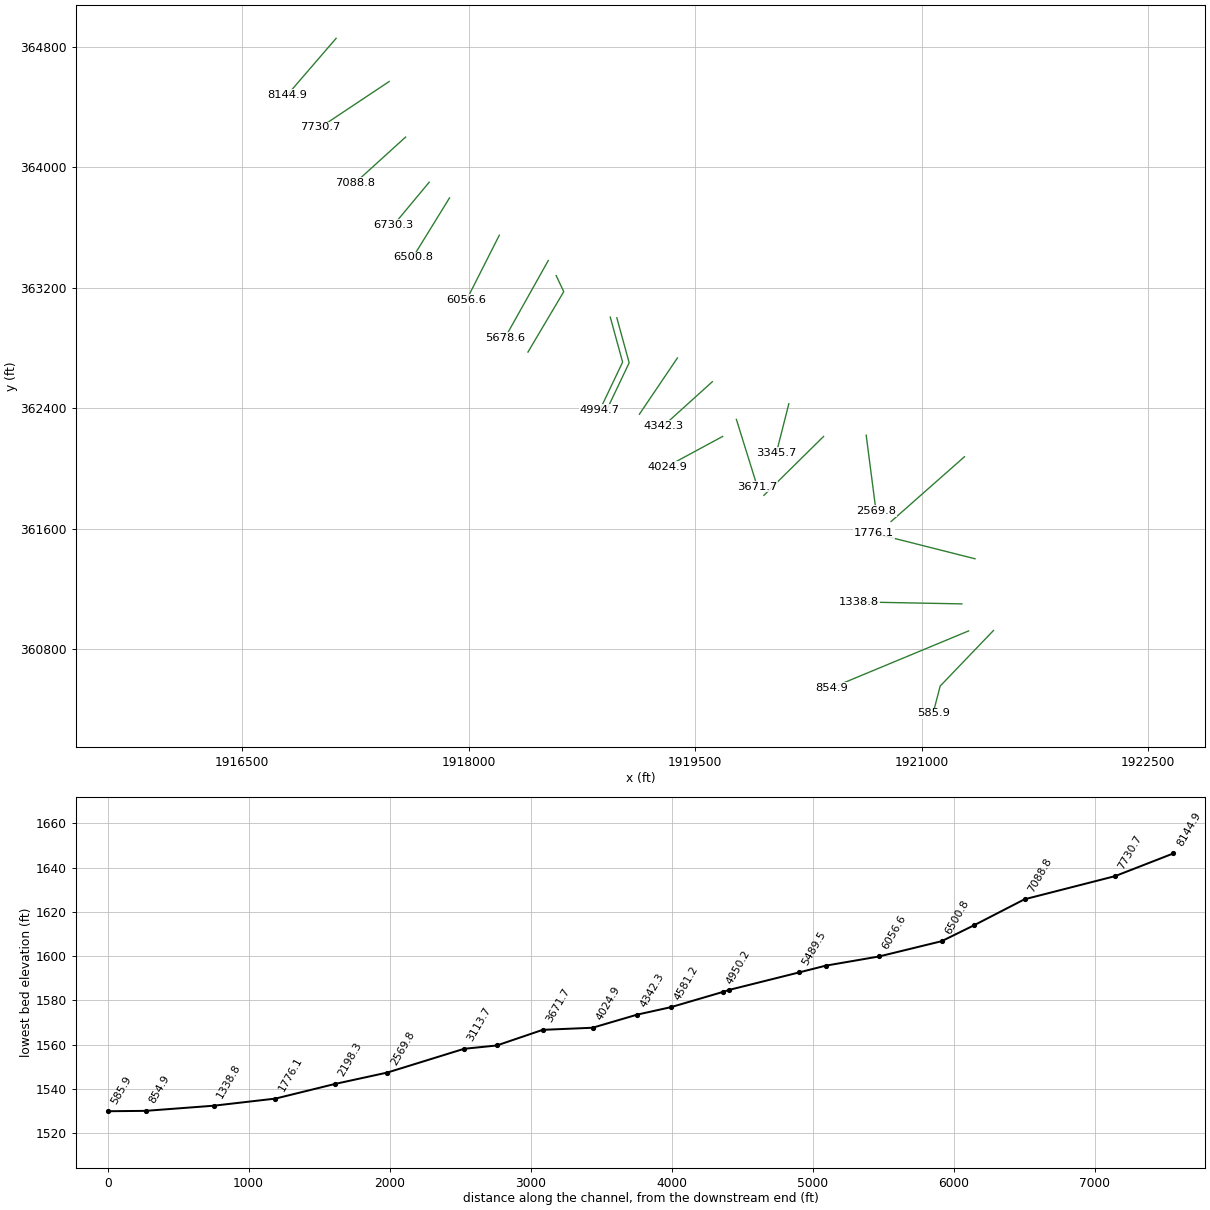
HEC-RAS study NP2.prj: NP2

--- NP2.g01 (geometry) --- (continued)

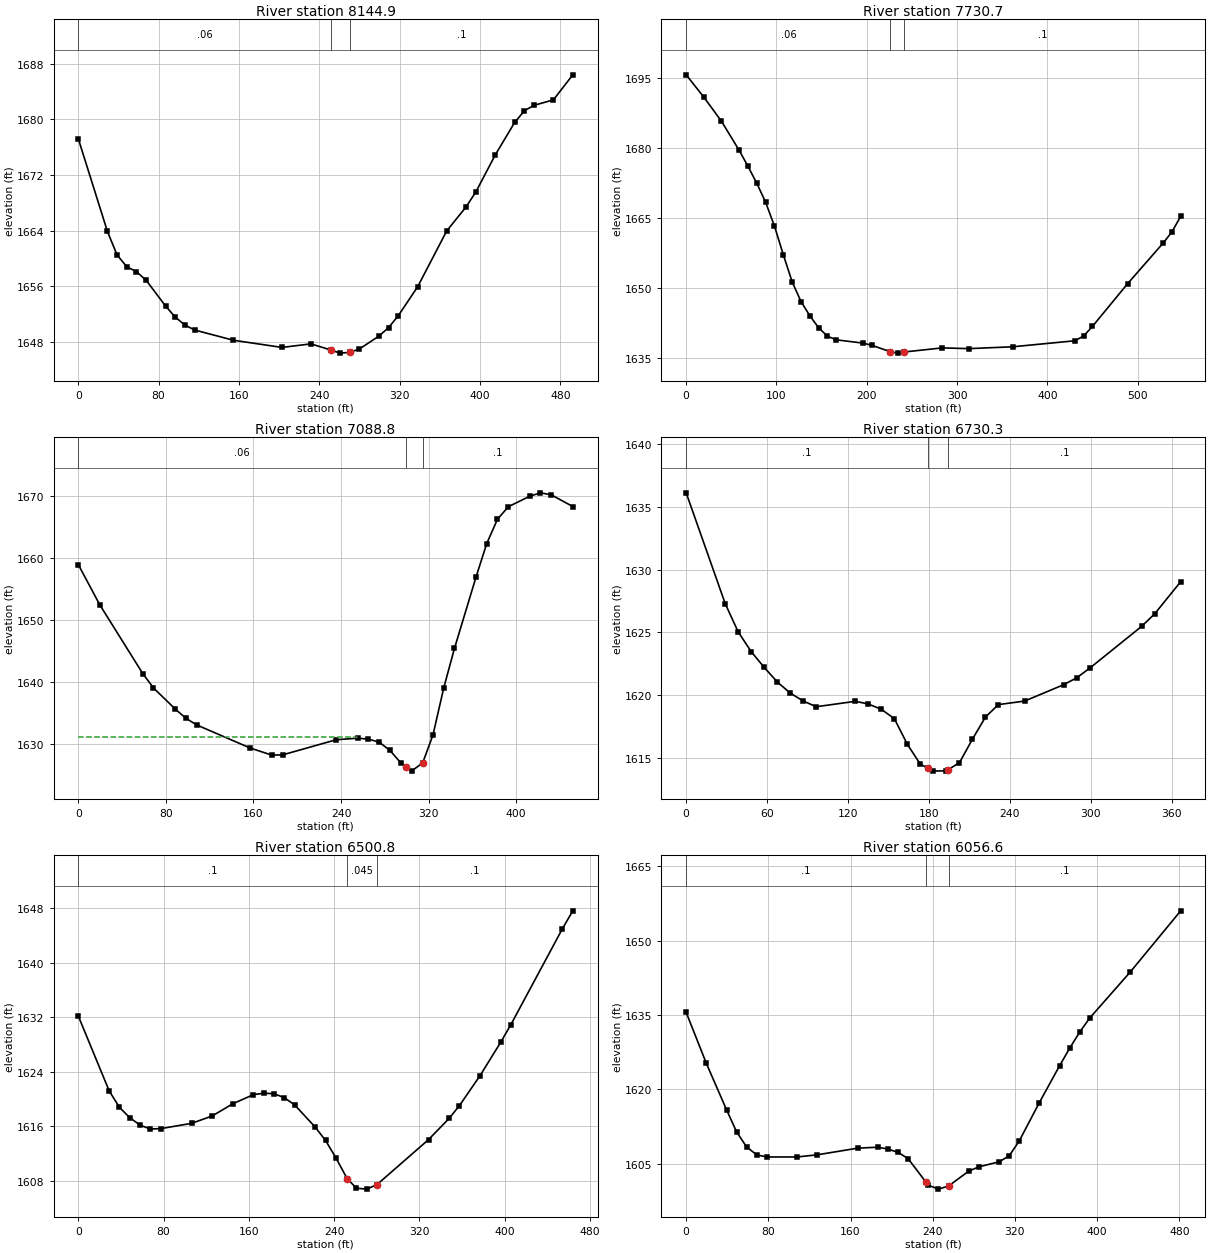
Type RM Length L Ch R = 1 ,8144.9  ,418.7,414.3,403.7
XS GIS Cut Line= 2
     1917122.003       364854.47     1916800.823      364481.206
#Sta/Elev= 30
       0 1677.23      29 1663.91    38.6 1660.53    48.3 1658.82    57.9 1658.12
    67.6 1656.88    86.9 1653.18    96.6 1651.58   106.2 1650.44   115.9 1649.73
   154.5 1648.26   202.8 1647.23   231.7 1647.74   251.7 1646.85   260.7 1646.41
   270.4 1646.52     280 1647.01   299.3 1648.85     309 1650.08   318.6 1651.78
   337.9 1655.94   366.9 1663.98   386.2 1667.43   395.9 1669.58   415.2 1674.89
   434.5 1679.55   444.2 1681.24   453.8 1682.02   473.1  1682.8   492.4  1686.4
#Mann= 3 , 0 , 0
       0     .06       0   251.7    .045       0   270.4      .1       0
Bank Sta=251.7,270.4
XS Rating Curve= 0 ,0
Exp/Cntr=0.3,0.1

Type RM Length L Ch R = 1 ,7730.7  ,638.2,641.8,645.1
XS GIS Cut Line= 2
     1917473.566      364568.012     1917017.837      364264.193
#Sta/Elev= 30
       0 1695.65    19.6 1690.87    39.1 1685.72    58.7 1679.51    68.5 1676.06
    78.2 1672.47      88  1668.4    97.8  1663.3   107.6 1657.18   117.4 1651.37
   127.2 1647.17   136.9 1644.15   146.7 1641.56   156.5 1639.75   166.3 1638.98
   195.6 1638.29   205.4 1637.83   226.3 1636.43   234.7 1636.14   241.3 1636.38
   283.6 1637.26     313  1637.1   361.9  1637.5   430.4 1638.78   440.1 1639.78
   449.9 1641.84     489 1651.01   528.2 1659.66   537.9 1662.03   547.7  1665.4
#Mann= 3 , 0 , 0
       0     .06       0   226.3    .045       0   241.3      .1       0
Bank Sta=226.3,241.3
XS Rating Curve= 0 ,0
Exp/Cntr=0.3,0.1

Type RM Length L Ch R = 1 ,7088.8  ,355.4,358.6,361.7
XS GIS Cut Line= 2
     1917582.073      364199.088     1917247.871      363895.269
#Sta/Elev= 30
       0 1658.92    19.6 1652.46    58.9 1641.39    68.7 1639.08    88.4 1635.71
    98.2 1634.21     108 1633.14   157.1 1629.41   176.7 1628.28   186.6 1628.31
   235.6 1630.75   255.3    1631   265.1 1630.84   274.9 1630.36   284.7 1629.02
   294.6 1627.04   299.6 1626.36   304.4  1625.7   314.6 1627.03     324 1631.52
   333.8 1639.06   343.6 1645.43   363.3  1656.9   373.1  1662.3   382.9  1666.2
   392.8 1668.21   412.4 1669.91   422.2 1670.45     432 1670.13   451.7 1668.25
#Mann= 3 , 0 , 0
       0     .06       0   299.6    .045       0   314.6      .1       0
#XS Ineff= 2 , 0
          254.93 1631.17
Permanent Ineff=
       F       F
Bank Sta=299.6,314.6
XS Rating Curve= 0 ,0
Exp/Cntr=0.3,0.1

Type RM Length L Ch R = 1 ,6730.3  ,226.3,229.4,232.4
XS GIS Cut Line= 2
     1917738.323      363899.609     1917503.948      363617.491
#Sta/Elev= 30
       0 1636.11      29 1627.27    38.6 1625.03    48.3 1623.45    57.9  1622.2
    67.6 1621.04    77.2 1620.16    86.9 1619.52    96.5 1619.07   125.5  1619.5
   135.1 1619.29   144.8 1618.86   154.4 1618.12   164.1 1616.07   173.7 1614.49
   179.2 1614.18   183.4 1613.94     193 1613.97   194.2 1614.05   202.7 1614.61
   212.3 1616.48     222 1618.25   231.6 1619.24     251 1619.52   279.9 1620.82
   289.6 1621.37   299.2 1622.13   337.8 1625.47   347.5 1626.47   366.8 1629.03
#Mann= 3 , 0 , 0
       0      .1       0   179.2    .045       0   194.2      .1       0
Bank Sta=179.2,194.2
XS Rating Curve= 0 ,0
Exp/Cntr=0.3,0.1

Type RM Length L Ch R = 1 ,6500.8  ,441.7,444.2,446.2
XS GIS Cut Line= 2
     1917872.871      363795.443     1917629.816      363400.477
#Sta/Elev= 30
       0  1632.2      29 1621.19    38.6 1618.78    48.3 1617.26      58 1616.16
    67.6  1615.6    77.3 1615.65   106.3 1616.43   125.6 1617.51   144.9  1619.3
   164.2 1620.64   173.9 1620.85   183.6 1620.78   193.2  1620.2   202.9 1619.14
   222.2 1615.88   231.9 1613.92   241.5  1611.4   252.3 1608.28   260.9 1606.91
   270.5 1606.77   280.2 1607.44   328.5 1614.04   347.8 1617.15   357.5 1619.03
   376.8 1623.43   396.1 1628.31   405.8 1630.94   454.1 1645.01   463.8 1647.63
#Mann= 3 , 0 , 0
       0      .1       0   252.3    .045       0   280.2      .1       0
Bank Sta=252.3,280.2
XS Rating Curve= 0 ,0
Exp/Cntr=0.3,0.1

Type RM Length L Ch R = 1 ,6056.6  ,377.9,378,376.8
XS GIS Cut Line= 2
     1918202.732      363548.047     1917985.719      363118.359
#Sta/Elev= 30
       0 1635.55    19.6 1625.27    39.3 1615.88    49.1 1611.43    58.9 1608.36
    68.8 1606.78    78.6 1606.36   108.1 1606.36   127.7  1606.8     167 1608.14
   186.7 1608.33   196.5 1607.95   206.3 1607.29   216.1 1606.02   233.4 1601.28
   235.8 1600.66   245.6 1599.87   255.4  1600.5   275.1  1603.5   284.9 1604.37
   304.6 1605.38   314.4 1606.58   324.2 1609.58   343.8 1617.33   363.5 1624.77
   373.3  1628.3   383.1 1631.57     393 1634.44   432.3 1643.69   481.4 1656.04
#Mann= 3 , 0 , 0
       0      .1       0   233.4    .045       0   255.4      .1       0
Bank Sta=233.4,255.4
XS Rating Curve= 0 ,0
Exp/Cntr=0.3,0.1

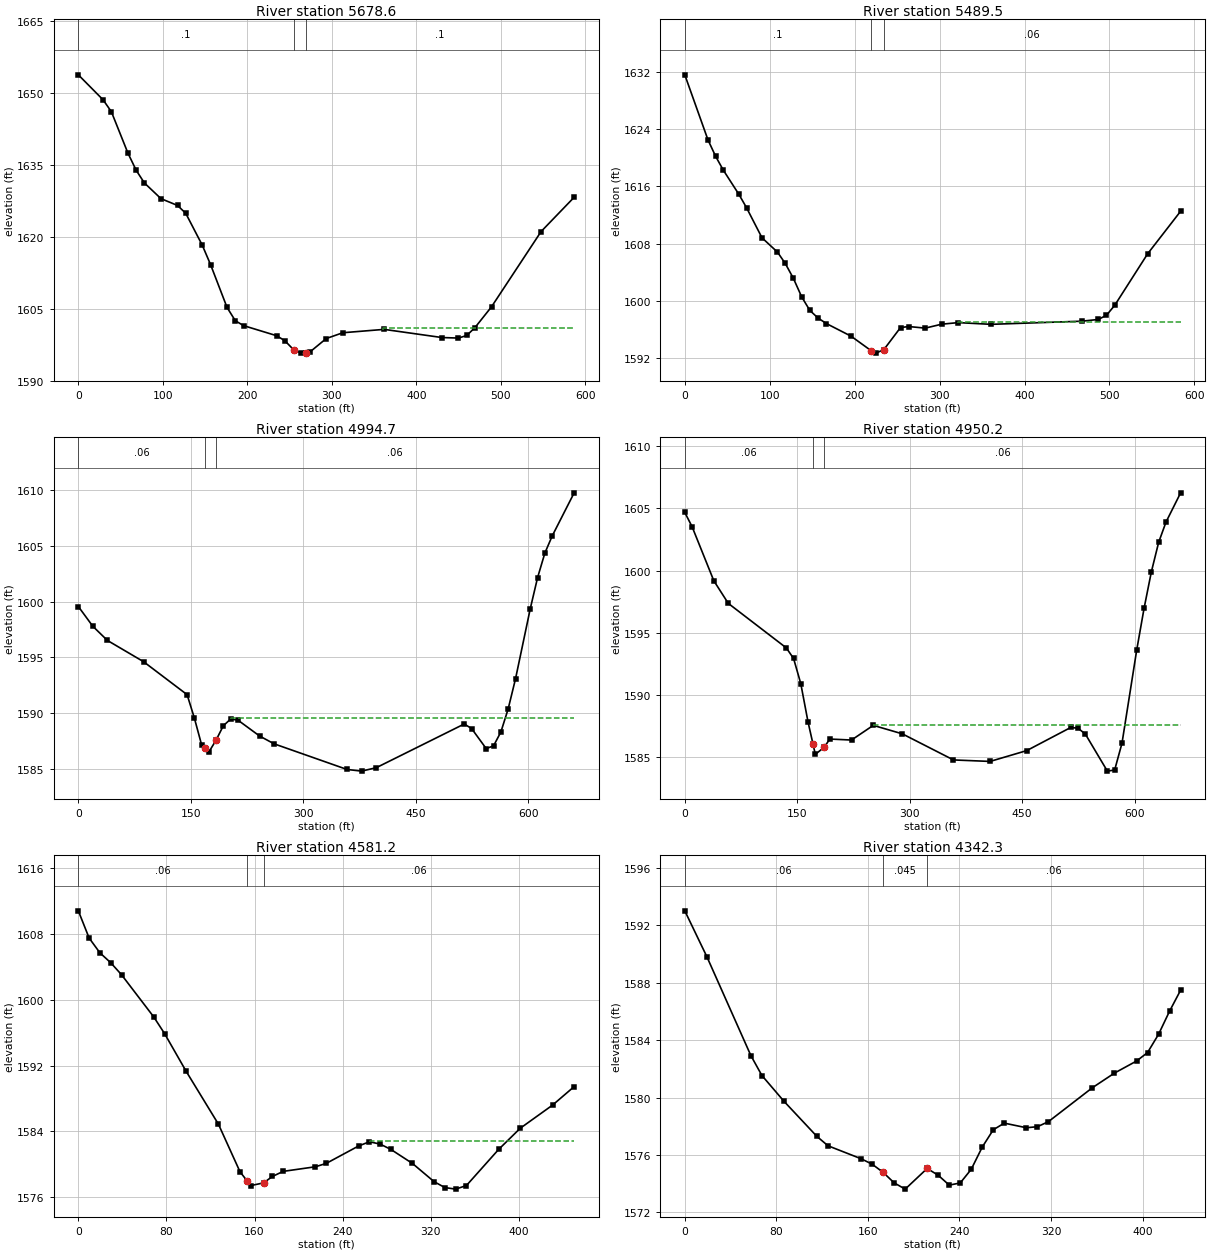
Type RM Length L Ch R = 1 ,5678.6  ,189.6,189.1,188.5
XS GIS Cut Line= 2
     1918527.017      363380.179     1918240.559      362868.026
#Sta/Elev= 30
       0 1653.73    29.3 1648.52    39.1 1646.04    58.7 1637.41    68.5 1633.82
    78.2 1631.19    97.8 1627.92   117.4  1626.5   127.1 1624.87   146.7 1618.21
   156.5 1614.17     176 1605.24   185.8 1602.47   195.6 1601.45   234.7 1599.35
   244.5 1598.29   254.8 1596.42   264.1 1595.72   269.8 1595.84   273.8 1595.92
   293.4 1598.76     313 1599.97   361.9 1600.67   430.3 1598.97   449.9 1598.86
   459.7  1599.4   469.5 1601.06     489 1605.38   547.7 1621.07   586.8 1628.21
#Mann= 3 , 0 , 0
       0      .1       0   254.8    .045       0   269.8      .1       0
#XS Ineff= 2 , 0
                             360         1601.01
Permanent Ineff=
       F       F
Bank Sta=254.8,269.8
XS Rating Curve= 0 ,0
Exp/Cntr=0.3,0.1

Type RM Length L Ch R = 1 ,5489.5  ,476,494.8,513.5
XS GIS Cut Line= 3
     1918579.101      363280.352     1918629.368      363173.427
     1918392.469       362772.54
#Sta/Elev= 30
       0 1631.61    27.3  1622.5    36.4 1620.18    45.4 1618.26    63.6  1614.9
    72.7 1613.01    90.9  1608.8   109.1  1606.8   118.2 1605.23   127.8 1603.14
   137.6 1600.54   147.2 1598.64     157 1597.56   166.7  1596.8   195.8 1595.03
   219.3 1593.01   224.9 1592.66   234.3 1593.14     254 1596.24   263.7 1596.38
   283.1 1596.16   302.5 1596.71   321.9 1596.93   360.7 1596.69   467.4 1597.13
   486.8 1597.37   496.5 1597.96   506.2 1599.35     545 1606.57   583.8 1612.52
#Mann= 3 , 0 , 0
       0      .1       0   219.3    .045       0   234.3     .06       0
#XS Ineff= 2 , 0
                          321.13         1597.03
Permanent Ineff=
       F       F
Bank Sta=219.3,234.3
XS Rating Curve= 0 ,0
Exp/Cntr=0.3,0.1

Type RM Length L Ch R = 1 ,4994.7  ,44.2,44.5,45
XS GIS Cut Line= 3
     1918937.527      363004.156     1919019.257      362705.664
     1918868.083      362387.837
#Sta/Elev= 30
       0 1599.56    19.3 1597.79    38.7 1596.52      87 1594.61   145.1 1591.65
   154.7 1589.57   164.4 1587.16   168.9 1586.85   174.1  1586.5   183.9 1587.59
   193.4 1588.86   203.1 1589.46   212.8 1589.37   241.8 1587.94   261.1 1587.24
   358.4 1584.94   377.9 1584.79   397.5  1585.1   514.8 1589.02   524.6 1588.61
   544.1 1586.81   553.9 1587.06   563.7 1588.31   573.4 1590.38   583.2 1593.08
   602.8 1599.35   612.6 1602.15   622.3 1604.35   632.1 1605.89   661.4 1609.76
#Mann= 3 , 0 , 0
       0     .06       0   168.9    .045       0   183.9     .06       0
#XS Ineff= 2 , 0
                           203.1          1589.6
Permanent Ineff=
       F       F
Bank Sta=168.9,183.9
XS Rating Curve= 0 ,0
Exp/Cntr=0.3,0.1

Type RM Length L Ch R = 1 ,4950.2  ,390.2,369,348
XS GIS Cut Line= 3
      1918980.93      362999.816      1919062.66      362701.324
     1918911.486      362383.497
#Sta/Elev= 30
       0 1604.67     9.7 1603.53    38.7 1599.18      58 1597.36   135.4 1593.78
   145.1 1592.93   154.7 1590.91   164.4 1587.82     171 1586.05   174.1 1585.22
     186 1585.79   193.4 1586.45   222.4 1586.37   251.4 1587.55   290.1 1586.87
   358.4 1584.77   407.2 1584.65   456.1 1585.52   514.8 1587.38   524.6 1587.32
   534.3 1586.85   563.7 1583.87   573.4 1583.96   583.2 1586.12   602.8  1593.6
   612.6 1596.95   622.3 1599.88   632.1 1602.27   641.9  1603.9   661.4 1606.25
#Mann= 3 , 0 , 0
       0     .06       0     171    .045       0     186     .06       0
#XS Ineff= 2 , 0
                          251.41         1587.57
Permanent Ineff=
       F       F
Bank Sta=171,186
XS Rating Curve= 0 ,0
Exp/Cntr=0.3,0.1

Type RM Length L Ch R = 1 ,4581.2  ,244.2,238.9,233.1
XS GIS Cut Line= 2
     1919382.052      362733.477     1919130.316      362360.213
#Sta/Elev= 30
       0 1610.84     9.8 1607.53    19.6 1605.73    29.4 1604.53    39.2 1603.07
    68.5 1597.93    78.3 1595.91    97.9 1591.32   127.2 1584.89   146.8  1579.1
   153.2    1578   156.6 1577.42   168.2 1577.75   176.2 1578.53     186 1579.15
   215.3 1579.71   225.1 1580.12   254.5 1582.24   264.3 1582.75     274 1582.47
   283.8 1581.82   303.4 1580.11     323  1577.9   332.8 1577.18   342.6 1576.99
   352.4 1577.43   381.7 1581.83   401.3  1584.4   430.6 1587.21   450.2 1589.46
#Mann= 3 , 0 , 0
       0     .06       0   153.2    .045       0   168.2     .06       0
#XS Ineff= 2 , 0
                          264.79         1582.83
Permanent Ineff=
       F       F
Bank Sta=153.2,168.2
XS Rating Curve= 0 ,0
Exp/Cntr=0.3,0.1

Type RM Length L Ch R = 1 ,4342.3  ,323.7,317.4,311.2
XS GIS Cut Line= 2
     1919613.323      362575.825     1919292.142      362285.026
#Sta/Elev= 30
       0 1593.02    19.3 1589.82    57.8 1582.92    67.4 1581.54    86.6 1579.75
   115.5 1577.29   125.2 1576.64     154 1575.74   163.7 1575.36   173.3 1574.79
   182.9 1574.06   192.6 1573.62   211.8 1575.06   221.4 1574.59   231.1  1573.9
   240.7 1574.05   250.3    1575     260 1576.56   269.6 1577.76   279.2 1578.22
   298.5  1577.9   308.1 1577.97   317.7 1578.32   356.2 1580.69   375.5 1581.71
   394.8 1582.55   404.4 1583.14     414 1584.41   423.6 1586.02   433.3 1587.49
#Mann= 3 , 0 , 0
       0     .06       0   173.3    .045       0   211.8     .06       0
Bank Sta=173.3,211.8
XS Rating Curve= 0 ,0
Exp/Cntr=0.3,0.1

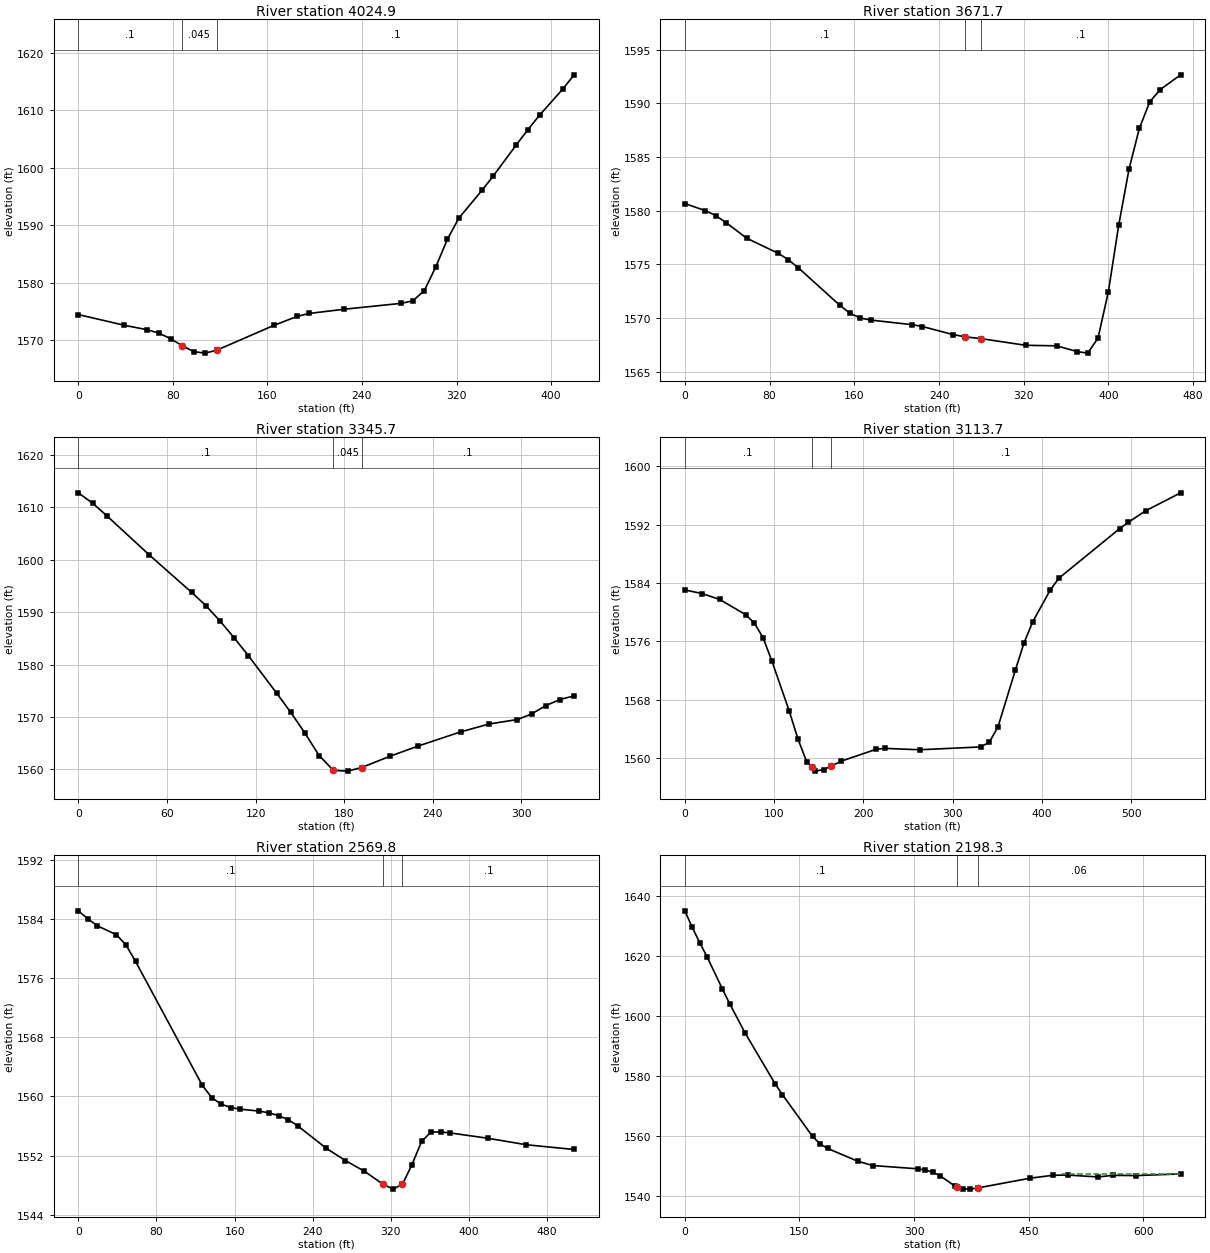
Type RM Length L Ch R = 1 ,4024.9  ,318.9,353.2,386.3
XS GIS Cut Line= 2
     1919681.531      362212.644     1919312.608      362012.991
#Sta/Elev= 26
       0 1574.41      39 1572.54    58.5 1571.76    68.3 1571.16      78 1570.22
    87.8 1568.99    97.6 1567.95   107.3 1567.69   117.1  1568.2   165.8 1572.56
   185.4 1574.11   195.1  1574.6   224.4 1575.33   273.2 1576.37   282.9  1576.8
   292.7 1578.58   302.4  1582.7   312.2 1587.51   321.9 1591.21   341.4 1596.04
   351.2  1598.6   370.7 1604.04   380.5 1606.67   390.2 1609.16   409.7 1613.68
   419.5  1616.2
#Mann= 3 , 0 , 0
       0      .1       0    87.8    .045       0   117.1      .1       0
Bank Sta=87.8,117.1
XS Rating Curve= 0 ,0
Exp/Cntr=0.3,0.1

Type RM Length L Ch R = 1 ,3671.7  ,339.5,326,312
XS GIS Cut Line= 2
     1919772.677      362325.491     1919911.566      361878.442
#Sta/Elev= 29
       0 1580.68    19.5 1580.01    29.3 1579.55      39  1578.9    58.5 1577.44
    87.8 1576.06    97.5 1575.46   107.3 1574.68   146.3  1571.2     156 1570.45
   165.8 1570.01   175.6 1569.82   214.6 1569.39   224.3 1569.22   253.6 1568.46
   264.7 1568.26   279.7 1568.09   321.8 1567.47   351.1 1567.42   370.6 1566.88
   380.4 1566.74   390.1 1568.14   399.9 1572.47   409.6 1578.64   419.4 1583.89
   429.1 1587.67   438.9 1590.14   448.6 1591.28   468.1 1592.67
#Mann= 3 , 0 , 0
       0      .1       0   264.7    .045       0   279.7      .1       0
Bank Sta=264.7,279.7
XS Rating Curve= 0 ,0
Exp/Cntr=0.3,0.1

Type RM Length L Ch R = 1 ,3345.7  ,244.2,231.9,219.4
XS GIS Cut Line= 2
     1920119.899      362429.658     1920037.434      362104.137
#Sta/Elev= 25
       0 1612.75     9.6 1610.79    19.2  1608.4      48 1600.92    76.8 1593.75
    86.4 1591.24    95.9 1588.33   105.5 1585.11   115.1 1581.72   134.3 1574.55
   143.9 1570.88   153.5 1566.91   163.1 1562.64   172.7 1559.84   182.3 1559.68
   191.9 1560.37   211.1 1562.52   230.3 1564.48     259 1567.17   278.2 1568.67
   297.4 1569.52     307 1570.59   316.6 1572.18   326.2 1573.33   335.8 1574.04
#Mann= 3 , 0 , 0
       0      .1       0   172.7    .045       0   191.9      .1       0
Bank Sta=172.7,191.9
XS Rating Curve= 0 ,0
Exp/Cntr=0.3,0.1

Type RM Length L Ch R = 1 ,3113.7  ,519.1,544,566.6
XS GIS Cut Line= 2
     1920349.934      362212.644     1919954.969      361822.019
#Sta/Elev= 30
       0 1583.03    19.5 1582.53      39 1581.73    68.2 1579.64      78 1578.48
    87.7 1576.47    97.5 1573.31     117 1566.43   126.7 1562.62   136.4  1559.5
  141.97 1558.75   146.2 1558.18   155.9  1558.4   164.2 1558.89   175.4 1559.55
   214.4 1561.18   224.2  1561.3   263.1 1561.11   331.4  1561.5   341.1 1562.13
   350.8 1564.22   370.3 1572.02   380.1 1575.78   389.8 1578.66   409.3 1582.99
   419.1 1584.64   487.3 1591.45     497 1592.32   516.5  1593.9   555.5 1596.35
#Mann= 3 , 0 , 0
       0      .1       0  141.97    .045       0   164.2      .1       0
Bank Sta=141.97,164.2
XS Rating Curve= 0 ,0
Exp/Cntr=0.3,0.1

Type RM Length L Ch R = 1 ,2569.8  ,393.8,371.5,348.9
XS GIS Cut Line= 2
     1920632.052      362221.324     1920697.156      361717.852
#Sta/Elev= 30
       0  1585.1     9.8 1584.01    19.5 1583.07      39 1581.87    48.8 1580.48
    58.6 1578.25   126.9 1561.51   136.7 1559.81   146.4 1558.95   156.2 1558.49
     166 1558.27   185.5 1558.01   195.3 1557.77     205  1557.4   214.8 1556.87
   224.5 1556.03   253.8 1552.99   273.4 1551.33   292.9 1549.88   311.8 1548.14
   322.2 1547.46   331.9 1548.12   341.7 1550.79   351.5 1553.91   361.2 1555.19
     371 1555.19   380.8 1555.06   419.8 1554.33   458.8 1553.46   507.7 1552.82
#Mann= 3 , 0 , 0
       0      .1       0   311.8    .045       0   331.9      .1       0
Bank Sta=311.8,331.9
XS Rating Curve= 0 ,0
Exp/Cntr=0.3,0.1

Type RM Length L Ch R = 1 ,2198.3  ,444.5,422.2,400.1
XS GIS Cut Line= 2
     1921283.094      362078.095     1920796.983      361648.408
#Sta/Elev= 30
       0 1635.01     9.8 1629.48    19.7 1624.33    29.5  1619.5    49.2 1608.98
      59 1603.94    78.6 1594.45     118 1577.47   127.8 1573.76   167.1 1559.88
   176.9  1557.4   186.8 1555.87   226.1 1551.63   245.8 1550.17   304.7 1549.08
   314.6 1548.68   324.4 1547.96   334.2 1546.73   353.9 1543.26   355.9 1543.08
   363.7 1542.37   373.6 1542.31   383.4 1542.71   452.2 1545.97   481.7 1546.92
   501.3 1546.99   540.7 1546.37   560.3  1546.9   589.8 1546.82   648.8 1547.37
#Mann= 3 , 0 , 0
       0      .1       0   355.9    .045       0   383.4     .06       0
#XS Ineff= 2 , 0
                          492.96         1547.45
Permanent Ineff=
       F       F
Bank Sta=355.9,383.4
XS Rating Curve= 0 ,0
Exp/Cntr=0.3,0.1

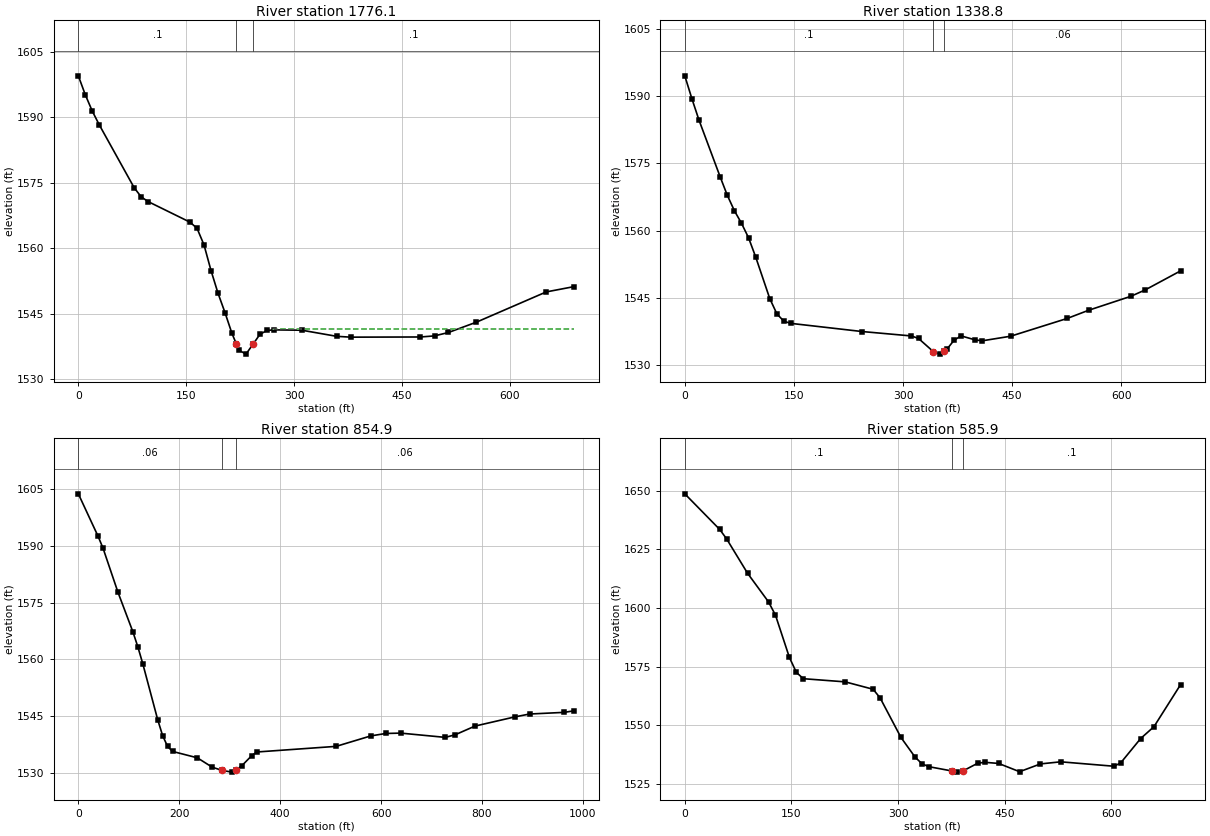
Type RM Length L Ch R = 1 ,1776.1  ,431.3,437.2,443.2
XS GIS Cut Line= 2
     1921352.538      361401.012     1920684.136      361570.283
#Sta/Elev= 30
       0 1599.49     9.7 1595.14    19.4  1591.4    29.1 1588.26    77.7 1573.83
    87.4 1571.75    97.1 1570.66   155.4 1565.94   165.1 1564.53   174.8 1560.72
   184.5 1554.86   194.2 1549.68   203.9 1545.24   213.6 1540.46   219.7 1538.06
   223.4  1536.6   233.1  1535.7   242.8 1537.94   252.5 1540.23   262.2 1541.12
   271.9 1541.26   310.8 1541.18   359.3 1539.78   378.7 1539.59   475.8 1539.63
   495.3 1539.88   514.7 1540.66   553.5 1543.02   650.7 1549.96   689.5 1551.18
#Mann= 3 , 0 , 0
       0      .1       0   219.7    .045       0   242.8      .1       0
#XS Ineff= 2 , 0
                          271.13         1541.49
Permanent Ineff=
       F       F
Bank Sta=219.7,242.8
XS Rating Curve= 0 ,0
Exp/Cntr=0.3,0.1

Type RM Length L Ch R = 1 ,1338.8  ,484.7,483.9,482.6
XS GIS Cut Line= 2
     1921265.733      361101.533     1920584.309      361114.554
#Sta/Elev= 30
       0 1594.51     9.7 1589.44    19.5 1584.65    48.7 1571.96    58.4  1567.9
    68.2 1564.44    77.9 1561.66    87.6 1558.44    97.4 1554.16   116.8 1544.87
   126.6 1541.46   136.3  1539.8     146 1539.34   243.4 1537.53   311.6 1536.54
   321.3 1535.98   341.8 1533.03   350.5 1532.49   356.8 1533.18   360.2 1533.56
     370 1535.56   379.7 1536.56   399.2 1535.66   408.9 1535.46   447.9 1536.48
   525.8 1540.45     555 1542.26   613.4 1545.39   632.9  1546.8   681.6 1551.05
#Mann= 3 , 0 , 0
       0      .1       0   341.8    .045       0   356.8     .06       0
Bank Sta=341.8,356.8
XS Rating Curve= 0 ,0
Exp/Cntr=0.3,0.1

Type RM Length L Ch R = 1 ,854.9   ,249.5,269,289
XS GIS Cut Line= 2
     1921310.371      360922.179     1920403.253      360544.575
#Sta/Elev= 30
       0 1603.83    39.3 1592.54    49.1 1589.38    78.6 1577.75   108.1 1567.31
   117.9 1563.34   127.7 1558.87   157.2 1544.08     167 1539.84   176.9 1536.95
   186.7 1535.64   235.8 1533.95   265.3 1531.47     285 1530.61   304.6 1530.16
   312.2 1530.67   324.2 1531.88   343.9 1534.56   353.7 1535.49   510.9 1536.98
   579.7 1539.75   609.2 1540.39   638.7 1540.49   727.1 1539.36   746.8 1540.05
   786.1 1542.35   864.7 1544.77   894.1 1545.54   962.9 1545.98   982.6  1546.4
#Mann= 3 , 0 , 0
       0     .06       0     285    .045       0   312.2     .06       0
Bank Sta=285,312.2
XS Rating Curve= 0 ,0
Exp/Cntr=0.3,0.1

Type RM Length L Ch R = 1 ,585.9   ,585.1,585.9,586.7
XS GIS Cut Line= 3
        1921475.         360925.      1921122.14      360556.334
        1921075.         360375.
#Sta/Elev= 30
       0 1648.75    49.1 1633.56    58.9  1629.5    88.3 1614.86   117.8 1602.64
   127.6 1596.97   147.2 1578.92     157 1572.55   166.8 1569.86   225.7 1568.51
     265 1565.35   274.8 1561.68   304.2 1544.77   323.9 1536.46   333.7 1533.55
   343.5 1532.31   376.5 1530.45   382.7 1529.99   391.5 1530.52   412.2 1533.79
     422 1534.18   441.6  1533.7   471.1 1530.17   500.5  1533.5     529 1534.39
     604  1532.5   613.4 1533.94   641.5 1544.34   660.2 1549.39   697.7 1567.36
#Mann= 3 , 0 , 0
       0      .1       0   376.5    .045       0   391.5      .1       0
Bank Sta=376.5,391.5
XS Rating Curve= 0 ,0
Exp/Cntr=0.3,0.1

Chan Stop Cuts=-1
Use User Specified Reach Order=0
Composite Channel Slope=5